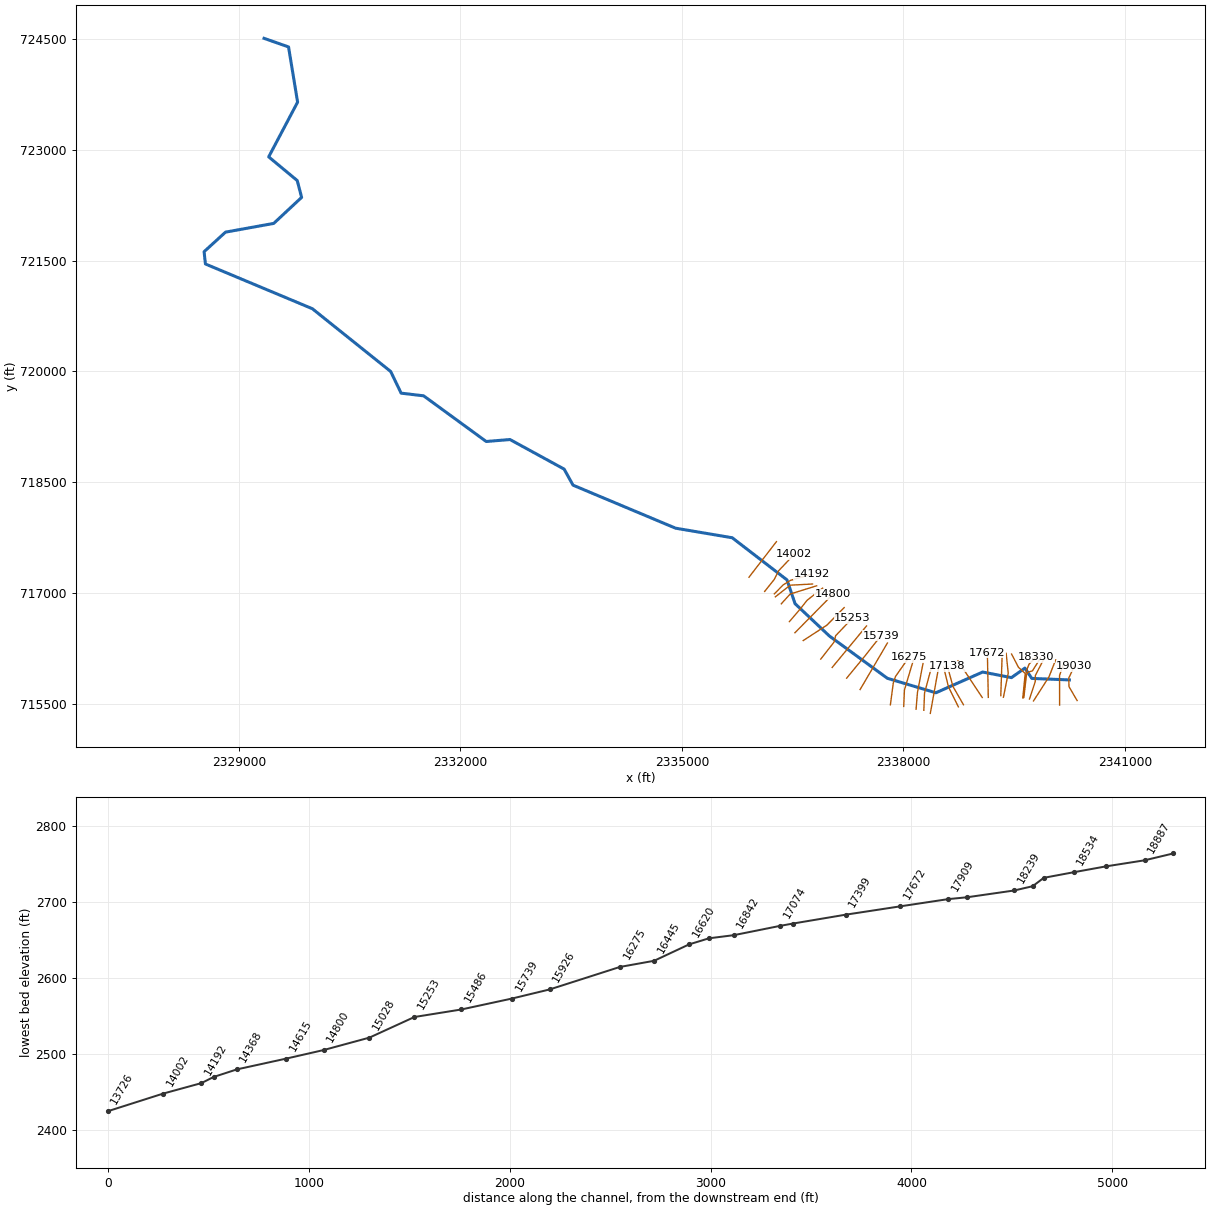
--- LTBLACKFK.prj (project) ---

Proj Title=LTBLACKFK
Current Plan=p01
Default Exp/Contr=0,0
English Units
Geom File=g01
Flow File=f01
Plan File=p01
BEGIN DESCRIPTION:
----------MODEL BY WOOD PLC 2022----------
AFH study
Randolph County, WV
HEC-RAS Version: RAS 6.2
Vertical Datum: NAVD88
Projection: NAD 1983 StatePlane West Virginia S FIPS 4702 (US Feet)
Terrain: 1-meter LIDAR (FEMA Region III 3DEP collected 2016-2018)
Land Use: 2019 NLCD
Hydrologic Method:
WV SIR2010-5033 regression equations
Additional Model Notes:
None
END DESCRIPTION:
DSS Export Rating Curves= 0
DSS Export Rating Curve Sorted= 0
DSS Export Volume Flow Curves= 0
DXF OffsetX= 0
DXF OffsetY= 0
DXF ScaleX= 0
DXF ScaleY= 0

--- LTBLACKFK.p01 (plan) ---

Plan Title=Floodplain
Program Version=6.20
Short Identifier=Floodplain
Geom File=g01
Flow File=f01
Subcritical Flow
K Sum by GR= 0
Std Step Tol= 0.01
Critical Tol= 0.01
Num of Std Step Trials= 20
Max Error Tol= 0.3
Flow Tol Ratio= 0.001
Split Flow NTrial= 30
Split Flow Tol= 0.02
Split Flow Ratio= 0.02
Log Output Level= 0
Friction Slope Method= 1
Unsteady Friction Slope Method= 2
Unsteady Bridges Friction Slope Method= 1
Parabolic Critical Depth
Global Vel Dist= 0 , 0 , 0
Global Log Level= 0
CheckData=True
Encroach Param=-1 ,0,0, 0
Mapping Interval=1HOUR
Computation Time Step Use Courant=        0
Computation Time Step Use Time Series=    0
Computation Time Step Count To Double=0
Computation Time Step Max Doubling=0
Computation Time Step Max Halving=0
Computation Time Step Residence Courant=0
Run HTab= 0
Run UNet= 0
Run Sediment= 0
Run PostProcess= 0
Run WQNet= 0
Run RASMapper=-1
UNET Theta= 0
UNET Theta Warmup= 0
UNET ZTol= 0
UNET ZSATol= 0
UNET MxIter= 0
UNET Max Iter WO Improvement= 0
UNET MaxInSteps= 0
UNET DtIC= 0
UNET DtMin= 0
UNET MaxCRTS= 0
UNET WFStab= 0
UNET SFStab= 0
UNET WFX= 1
UNET SFX= 1
UNET Gravity=32.174
UNET 1D Methodology=Finite Difference
UNET DSS MLevel= 1
UNET Pardiso=0
UNET DZMax Abort= 0
UNET Use Existing IB Tables= 0
UNET Froude Reduction=False
UNET Froude Limit= 0
UNET Froude Power= 0
UNET D1 Cores= 0
UNET WindReference=Eulerian
UNET WindDragFormulation=Hsu (1988)
UNET D2 Coriolis=0
UNET D2 Cores= 0
UNET D2 Theta= 1
UNET D2 Theta Warmup= 1
UNET D2 Z Tol= 0.01
UNET D2 Volume Tol= 0.01
UNET D2 Max Iterations= 20
UNET D2 Equation= 0
UNET D2 RampUpFraction=0.1
UNET D2 TimeSlices= 1
UNET D2 Turbulence Formulation=Non-Conservative (original)
UNET D2 Eddy Viscosity=0.3
UNET D2 Transverse Eddy Viscosity=0.1
UNET D2 Smagorinsky Mixing=0
UNET D2 BCVolumeCheck=0
UNET D2 Cores=0
UNET D2 SolverType=PARDISO (Direct)
UNET D2 Minimum Iterations= 2147483647
UNET D2 Maximum Iterations= 2147483647
UNET D2 Restart Number= 10
UNET D2 Relaxation Coeff=1.3
UNET D2 SOR Precondition Iterations= 10
UNET D2 ILUT Maximum Fill= 8
UNET D2 ILUT Tolerance=1E-08
UNET D1D2 MaxIter= 0
UNET D1D2 ZTol=0.01
UNET D1D2 QTol=0.1
UNET D1D2 MinQTol=1
Write IC File= 0
Write IC File at Fixed DateTime=0
Write IC File at Sim End=0
Echo Input=False
Echo Parameters=False
Echo Output=False
Write Detailed= 0
HDF Write Warmup=0
HDF Write Time Slices=0
HDF Flush=0
HDF Compression= 1
HDF Chunk Size= 1
HDF Spatial Parts= 1
HDF Use Max Rows=0
HDF Fixed Rows= 1
Calibration Method= 0
Calibration Iterations= 20
Calibration Max Change=0.05
Calibration Tolerance=0.2
Calibration Maximum=1.5
Calibration Minimum=0.5
Calibration Optimization Method= 1
WQ AD Non Conservative
WQ ULTIMATE=-1
WQ Max Comp Step=1HOUR
WQ Output Interval=15MIN
WQ Output Selected Increments= 0
WQ Output face flow=0
WQ Output face velocity=0
WQ Output face area=0
WQ Output face dispersion=0
WQ Output cell volume=0
WQ Output cell surface area=0
WQ Output cell continuity=0
WQ Output cumulative cell continuity=0
WQ Output face conc=0
WQ Output face dconc_dx=0
WQ Output face courant=0
WQ Output face peclet=0
WQ Output face adv mass=0
WQ Output face disp mass=0
WQ Output cell mass=0
WQ Output cell source sink temp=0
WQ Output nsm pathways=0
WQ Output nsm derived pathways=0
WQ Create Restart=0
WQ Fixed Restart=0
WQ System Summary=0
WQ Write To DSS=0
Sorting and Armoring Iterations= 10
XS Update Threshold= 0.02
Bed Roughness Predictor= 0
Hydraulics Update Threshold= 0.02
Energy Slope Method= 1
Volume Change Method= 1
Sediment Retention Method= 0
Sediment TS Multiplier= 1
Warm Up Method= 0
XS Weighting Method= 0
Number of US Weighted Cross Sections= 1
Number of DS Weighted Cross Sections= 1
Upstream XS Weight=0
Main XS Weight=1
Downstream XS Weight=0
Number of DS XS's Weighted with US Boundary= 1
Upstream Boundary Weight= 1
Weight of XSs Associated with US Boundary= 0
Number of US XS's Weighted with DS Boundary= 1
Downstream Boundary Weight= 0.5
Weight of XSs Associated with DS Boundary= 0.5
Percentile Method= 0
Sediment Output Level= 3
Mass or Volume Output= 0
Output Increment Type= 1
Profile and TS Output Increment= 1
Transport Output Increment 1
XS Output Flag= 0
XS Output Increment= 10
Read HDF5 Sediment Hotstart= 0
Sediment Hotstart Type= 0
Write Gradation File= 0
Read Gradation Hotstart= 0
Write HDF5 File= 1
Write Binary Output= 1
Write DSS Sediment File= 0
DSS Sediment Output Type= 1
SV Curve= 0
Specific Gage Flag= 0
Subcell Erosion Methods= 0
Subcell Deposition Methods= 0
Advection Scheme= 1
Matrix Solver= 0
Implicit Weighting Factor= 1
Maximum Outer Loop Convergence Iterations= 5
Convergence Maximum Absolute= 0.001
Convergence RMSE= 0.0001
Grain Fractions Max Abs Error= 0.001
Max Subgrid Regions= 1
Max Subgrid Length Scale= 3.402823E+38
Initial Layer Thickness= 3.402823E+38
Min Layer Thickness= 3.402823E+38
Max Layer Thickness= 3.402823E+38
Number of Layers= 5

--- LTBLACKFK.f01 (steady flow) ---

Flow Title=Flow
Program Version=6.20
Number of Profiles= 1
Profile Names=P100yr
River Rch & RM=LTBLACKFK,Main,19030
     524
River Rch & RM=LTBLACKFK,Main,16275
     602
River Rch & RM=LTBLACKFK,Main,13726
     673
River Rch & RM=LTBLACKFK,Main,11753
     748
River Rch & RM=LTBLACKFK,Main,8939
     844
River Rch & RM=LTBLACKFK,Main,5094
    1040
Boundary for River Rch & Prof#=LTBLACKFK,Main            , 1
Up Type= 0
Dn Type= 3
Dn Slope=0.02816
DSS Import GetInterval= 0
DSS Import GetPeak= 0
DSS Import FillOption= 0

--- LTBLACKFK.g01 (geometry) ---

Geom Title=Geometry
Program Version=6.20

River Reach=LTBLACKFK       ,Main
Reach XY= 30
2340248.85037806715819.7984864522339739.77073671715840.197053178
     2339646.649      715980.0482339463.59501603715850.841680487
     2339073.749      715926.619     2338439.937      715645.456
     2337783.092      715841.958     2336998.215      716414.135
     2336532.661      716852.375     2336423.285      717174.771
2335680.97118597 717745.71559327     2334913.807      717875.326
     2333524.406      718458.185     2333404.447      718675.413
2332670.52054849719076.2536757022332348.53226181719049.799686945
      2331501.02      719668.289     2331195.908      719704.667
     2331054.774      719997.803     2329993.652      720848.238
     2328544.933      721454.462     2328526.769      721620.812
2328817.03610539  721885.7029258     2329469.935      722004.011
     2329847.895      722356.585     2329788.581      722584.547
     2329401.986      722905.445     2329793.598      723646.628
     2329670.827      724394.702     2329338.878       724511.22

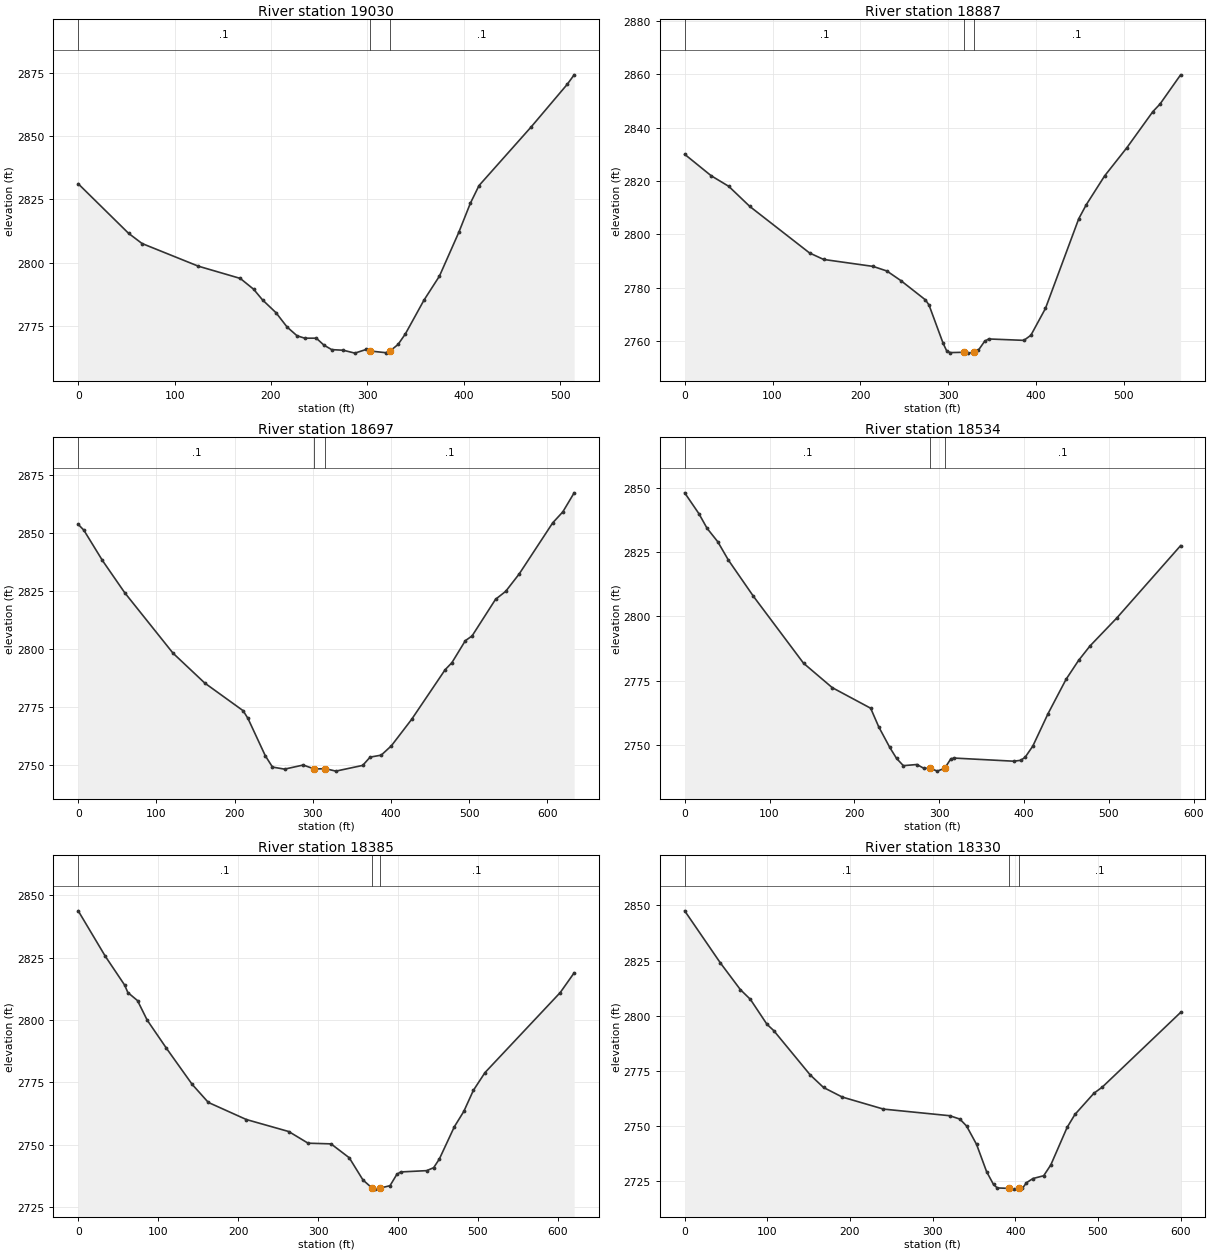
Type RM Length L Ch R = 1 ,19030   ,142,143.4,142.8
XS GIS Cut Line= 4
 2340353.6284135715540.1068271872340243.18645002715728.876424348
2340240.83662101715845.5845985272340316.81442567716007.722800239
#Sta/Elev= 30
       0 2831.19    52.2 2811.69    66.2 2807.66   124.6 2798.73   168.1 2793.91
     182 2789.64   191.2 2785.45   205.2  2780.4   216.7 2774.76     227 2771.32
     235 2770.37     247 2770.37     255  2767.6     263 2765.86     275 2765.62
     287 2764.48     299 2765.96   302.32765.334     319 2764.66  323.58 2765.34
   331.8 2767.89   339.4 2772.05   358.7 2785.35   374.7 2794.79   394.8 2812.03
   406.8  2823.5   415.8 2830.48     470 2853.62   507.3 2870.35   514.5  2874.1
#Mann= 3, -1 ,  0
       0     0.1       0   302.3   0.045       0  323.58     0.1       0
Bank Sta=302.3,323.58
XS Rating Curve= 0 ,0
Exp/Cntr(USF)=0,0
Exp/Cntr=0.3,0.1

Type RM Length L Ch R = 1 ,18887   ,194.5,190.4,186.7
XS GIS Cut Line= 3
2340116.29568346715479.0112729192340115.51240712715878.482204671
2340167.99192169716035.137472025
#Sta/Elev= 30
       0 2830.03    30.2 2821.97    50.2    2818    74.2 2810.44   142.2 2792.99
   158.2 2790.56   214.5 2787.95   230.2 2786.23   246.2 2782.61   274.2 2775.37
   278.2 2773.46   294.2 2759.15   298.2 2756.34   302.2  2755.6   318.2 2755.72
   322.2  2755.4  329.08 2755.74   334.2 2756.39   341.6 2759.87   346.2 2760.72
   386.2 2760.19   394.2 2762.11   410.8 2772.18   448.7 2805.84   457.2 2811.06
   478.2 2821.93   503.6 2832.54   533.1 2846.05   541.2 2848.87   564.7 2859.85
#Mann= 3, -1 ,  0
       0     0.1       0   318.2   0.045       0  329.08     0.1       0
Bank Sta=318.2,329.08
XS Rating Curve= 0 ,0
Exp/Cntr(USF)=0,0
Exp/Cntr=0.3,0.1

Type RM Length L Ch R = 1 ,18697   ,157.7,162.3,165.6
XS GIS Cut Line= 3
2339762.74675872715535.1332806372339972.51746586 715861.33931093
 2340062.9931747716090.734196466
#Sta/Elev= 30
       0 2853.89     7.2 2851.38      31 2838.31    59.5 2824.41   121.3 2798.34
   161.9 2785.46   210.9 2773.56   217.1 2770.24   239.3 2754.14   248.5 2749.24
     264 2748.35   287.8 2750.12     302 2748.42   316.3 2748.54   329.6 2747.49
   363.9 2749.96   373.4 2753.53   387.6 2754.38   400.6 2758.41   426.4 2769.76
   469.4 2791.23     478 2794.24   495.2 2803.74   503.8 2805.77   533.9  2821.6
   546.8 2824.99     564 2832.46     607 2854.55   619.9 2859.27   634.4 2867.48
#Mann= 3, -1 ,  0
       0     0.1       0     302   0.045       0   316.3     0.1       0
Bank Sta=302,316.3
XS Rating Curve= 0 ,0
Exp/Cntr(USF)=0,0
Exp/Cntr=0.3,0.1

Type RM Length L Ch R = 1 ,18534   ,157.2,149.2,139.5
XS GIS Cut Line= 4
2339708.10337359715560.1648375932339786.50969249715796.608893038
2339787.73479123715879.9156068742339902.89407212 716104.10867499
#Sta/Elev= 30
       0 2848.18    16.7 2840.09    26.4 2834.35      39 2829.11    51.6 2821.92
    81.1 2807.81   140.1 2781.75   173.9 2772.24   219.2 2764.21   228.7 2756.96
   241.7 2748.94   249.7 2744.66   257.7 2741.82   273.7 2742.27   281.7 2740.82
   289.7 2740.77   297.7 2739.69   306.42740.795   313.7 2744.49   317.7 2744.78
   387.8 2743.56   396.1 2743.91   401.3 2745.12   410.3 2749.45   428.3 2762.13
   449.5 2775.49   464.2 2782.83   477.7 2788.49     509 2799.29   584.5  2827.6
#Mann= 3, -1 ,  0
       0     0.1       0   289.7   0.045       0   306.4     0.1       0
Bank Sta=289.7,306.4
XS Rating Curve= 0 ,0
Exp/Cntr(USF)=0,0
Exp/Cntr=0.3,0.1

Type RM Length L Ch R = 1 ,18385   ,50.6,55.2,60.2
XS GIS Cut Line= 5
2339632.23581793 715583.465072222339666.44022617715882.127953879
2339684.20114128715921.3418996192339748.79228315715943.391614396
2339859.98712154716119.890303803
#Sta/Elev= 30
       0 2843.73    33.9 2825.54    58.1    2814    62.1 2811.02    74.2 2807.79
    86.3 2799.97   110.4  2788.7   142.6 2774.24   162.8 2767.02   210.4 2760.17
   263.4 2755.37   287.6  2750.7   316.3 2750.43   339.1 2744.87   356.3 2735.97
   367.72732.729   371.9 2732.31   377.4  2732.7   390.1 2733.69   398.6 2738.19
   403.4 2739.19     436 2739.71   444.7 2740.89   451.8 2744.35   470.7 2757.34
   482.4  2763.4   494.4 2771.85     509 2778.99   603.1 2811.02   620.5  2818.9
#Mann= 3, -1 ,  0
       0     0.1       0   367.7   0.045       0   377.4     0.1       0
Bank Sta=367.7,377.4
XS Rating Curve= 0 ,0
Exp/Cntr(USF)=0,0
Exp/Cntr=0.3,0.1

Type RM Length L Ch R = 1 ,18330   ,79.3,91.1,100.7
XS GIS Cut Line= 4
2339624.54879269715578.1780012222339664.73086877715939.816685908
2339702.09315003716032.1649660132339797.26122495716130.152835743
#Sta/Elev= 30
       0 2847.54    43.3 2823.85    67.4 2811.79    79.5 2807.38    99.6 2796.05
   107.7 2793.23   151.9 2773.09     168  2767.4   190.7 2763.05   240.5 2757.59
   320.8 2754.58     333 2753.05   341.1 2749.92   353.2 2741.57   365.3 2729.24
   373.7 2723.38   378.3 2721.82   392.1 2721.62   398.3 2721.28   404.4  2721.6
   408.5 2721.57   413.6 2724.19   421.4 2726.09   434.4 2727.35     443 2732.25
   462.8 2749.31   472.2 2755.15   495.2 2764.78   505.3 2767.56   600.1 2801.45
#Mann= 3, -1 ,  0
       0     0.1       0   392.1   0.045       0   404.4     0.1       0
Bank Sta=392.1,404.4
XS Rating Curve= 0 ,0
Exp/Cntr(USF)=0,0
Exp/Cntr=0.3,0.1

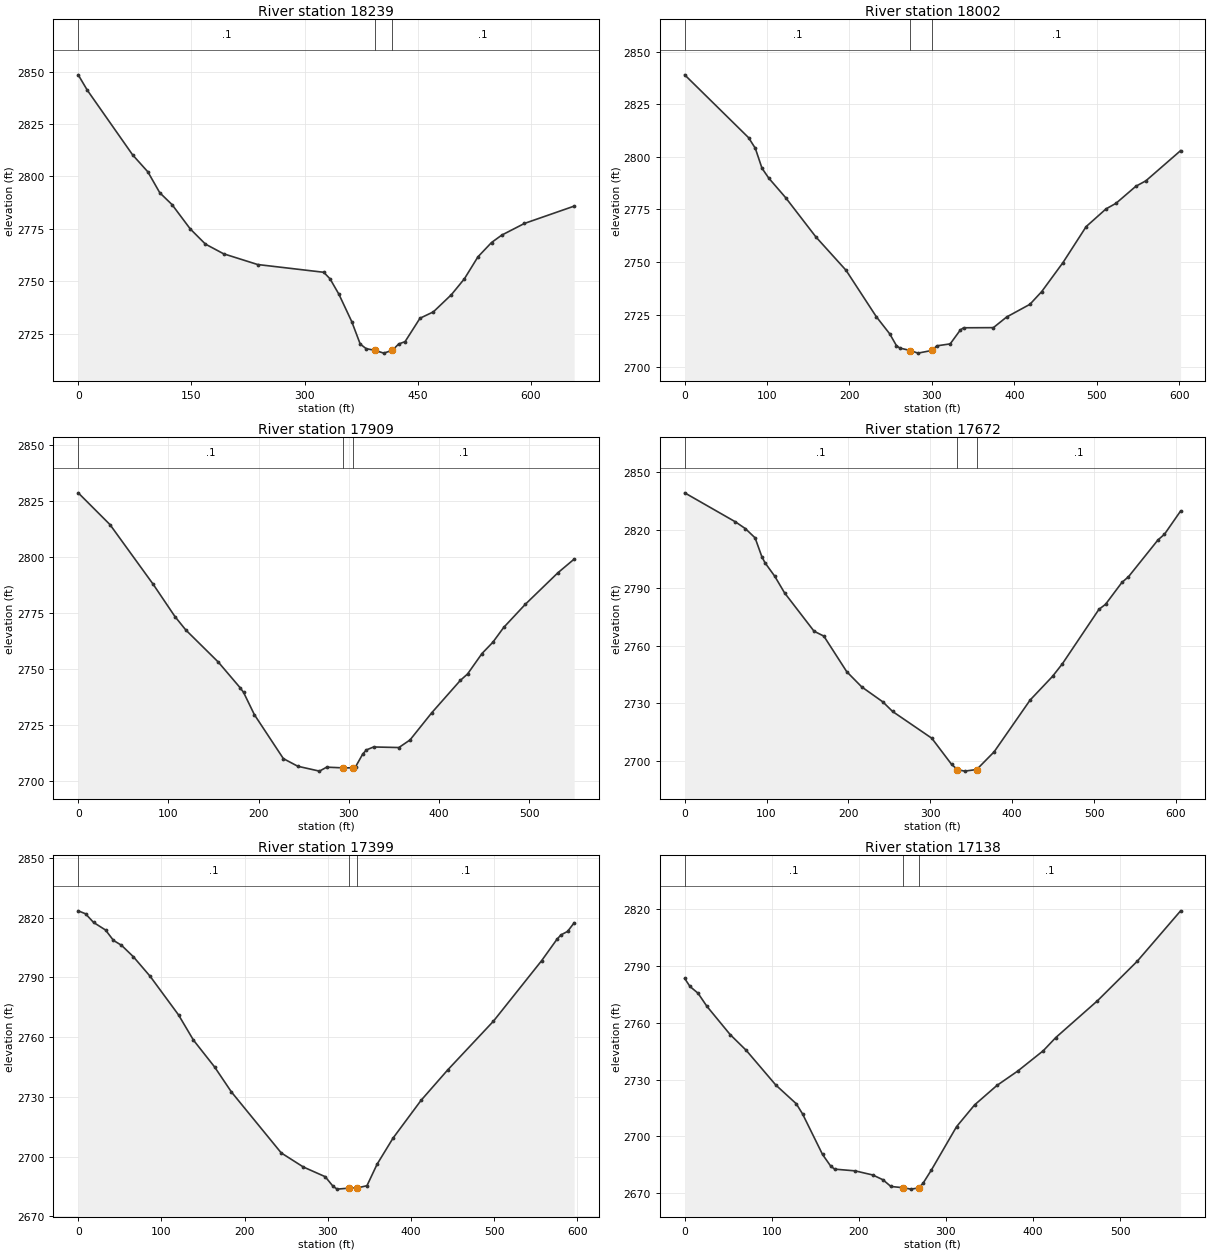
Type RM Length L Ch R = 1 ,18239   ,247.3,236.9,223.1
XS GIS Cut Line= 4
2339617.78599422715577.3584481292339650.18608769715906.860271624
2339558.64132818715991.3995915662339465.82950003716170.419149061
#Sta/Elev= 30
       0 2848.43    11.9 2841.18    72.2  2810.2    92.3 2802.15   108.1 2792.17
   124.4  2786.5   148.5 2774.91   168.6 2767.68   192.7 2763.05   237.8 2757.93
   325.4 2754.23   333.8 2751.09   345.5 2743.76   362.5 2730.72   373.8 2719.96
   381.7 2717.79   393.7 2716.96   404.9 2715.66   416.32716.985   424.7 2720.01
   433.2 2721.14     453 2732.31   470.7 2735.34   494.5 2743.51   511.8  2751.1
   529.8  2761.6   547.8 2768.43   561.3 2771.95   591.4 2777.53   657.3 2785.79
#Mann= 3, -1 ,  0
       0     0.1       0   393.7   0.045       0   416.3     0.1       0
Bank Sta=393.7,416.3
XS Rating Curve= 0 ,0
Exp/Cntr(USF)=0,0
Exp/Cntr=0.3,0.1

Type RM Length L Ch R = 1 ,18002   ,93.6,92.7,91.1
XS GIS Cut Line= 3
   2339355.27258715585.1669569822339420.20517136715911.768173929
2339392.61806878716179.137781873
#Sta/Elev= 30
       0 2839.07    77.5 2809.18    85.7 2804.12    93.8 2794.64     102 2789.94
   122.4 2780.68   159.1 2761.99   195.8 2746.06   232.5    2724   248.8 2715.82
   256.9 2710.25     261 2709.06   273.7 2707.89   283.1 2706.64   300.1 2707.93
   305.9  2710.1   322.2 2711.04   334.5 2717.65   338.4  2718.7   374.6 2718.77
   390.7 2723.83   418.9 2729.86   433.2  2735.9   459.1 2749.76   487.2 2766.86
   511.3 2775.28   523.4 2777.93   547.5 2786.05   559.6 2788.62   601.8 2803.01
#Mann= 3, -1 ,  0
       0     0.1       0   273.7   0.045       0   300.1     0.1       0
Bank Sta=273.7,300.1
XS Rating Curve= 0 ,0
Exp/Cntr(USF)=0,0
Exp/Cntr=0.3,0.1

Type RM Length L Ch R = 1 ,17909   ,232.5,237.3,232.5
XS GIS Cut Line= 2
2339319.67836836715606.0456957182339338.00703464716155.200735425
#Sta/Elev= 30
       0 2828.44    35.2 2814.26    83.2 2787.55   107.2 2773.22   119.2 2767.24
   155.2 2752.92   179.2 2741.56   183.2  2739.4   195.2 2729.44   227.3 2709.84
   243.3 2706.42   267.3 2704.25   275.3 2706.02  293.25 2705.71     305 2705.72
   307.3 2706.19   315.3 2711.91   319.3 2713.71   327.3 2715.03   355.3 2714.78
   367.6 2718.15   391.9 2730.38   423.4 2744.74   431.4  2747.6   447.4 2756.74
   459.4 2761.75   471.4 2768.35   495.4  2778.7   531.4 2792.73   549.5 2798.86
#Mann= 3, -1 ,  0
       0     0.1       0  293.25   0.045       0     305     0.1       0
Bank Sta=293.25,305
XS Rating Curve= 0 ,0
Exp/Cntr(USF)=0,0
Exp/Cntr=0.3,0.1

Type RM Length L Ch R = 1 ,17672   ,269.4,273.1,278.3
XS GIS Cut Line= 2
 2339150.4101934715583.2420162322339137.64863949716188.883333288
#Sta/Elev= 30
       0  2839.4      62 2824.31      74 2820.84      86 2816.01    94.2 2806.28
    98.1 2803.05     110 2796.07     122 2787.41     158  2767.5     170 2764.93
     198 2746.42   216.3 2738.53     242 2730.78     254 2725.77   301.9 2711.85
     326  2698.3   333.2 2695.55     342 2694.77   356.7  2695.6     378  2704.8
     422 2731.73   449.3    2744   461.5 2750.63     506 2778.83   514.1 2781.47
   534.1 2792.84   542.1 2795.78   578.1  2814.9   586.1 2817.89   605.8 2829.96
#Mann= 3, -1 ,  0
       0     0.1       0   333.2   0.045       0   356.7     0.1       0
Bank Sta=333.2,356.7
XS Rating Curve= 0 ,0
Exp/Cntr(USF)=0,0
Exp/Cntr=0.3,0.1

Type RM Length L Ch R = 1 ,17399   ,259.5,261,257.4
XS GIS Cut Line= 2
 2339067.9612206715581.8345619222338738.53633998716078.521165037
#Sta/Elev= 30
       0 2823.44     8.8 2821.96    18.4 2817.63    32.8 2813.82    42.4 2808.58
      52 2806.15    66.4 2800.34    86.5 2790.54   120.6 2771.17   138.4 2758.59
   163.9 2745.06   184.1 2732.52     244  2701.9   270.6 2694.83   296.8 2689.98
   306.4 2685.08   311.2 2683.73   325.5 2684.23   335.2 2684.33     347 2685.44
   359.2 2696.25   378.4 2709.38     412 2728.29   443.8 2743.46     499 2768.04
   556.9 2798.41   575.2 2809.08     580 2811.31   588.1 2813.11     596 2817.42
#Mann= 3, -1 ,  0
       0     0.1       0   325.5   0.045       0   335.2     0.1       0
Bank Sta=325.5,335.2
XS Rating Curve= 0 ,0
Exp/Cntr(USF)=0,0
Exp/Cntr=0.3,0.1

Type RM Length L Ch R = 1 ,17138   ,61.5,63.3,60.2
XS GIS Cut Line= 3
2338813.74900332715483.8915842262338671.83051022715730.821616165
2338595.94859168716005.209375824
#Sta/Elev= 30
       0 2783.43     6.1 2779.19    15.3 2775.65    25.5 2768.73    52.2 2753.79
    70.7 2745.43   104.6 2727.13   128.1 2717.24   135.3  2711.9   158.3 2690.42
   167.6 2684.31   172.2 2682.66   195.8 2681.75     216 2679.57   227.7 2677.04
   236.8  2673.5   250.4 2672.88   259.8  2672.1   268.92672.745   273.7 2675.18
   283.4 2682.28   312.2  2705.1   332.9  2716.6   358.5 2726.87   382.7 2734.58
   411.8 2745.25   426.2 2752.22     474 2771.64   519.7 2792.54   569.5 2819.17
#Mann= 3, -1 ,  0
       0     0.1       0   250.4   0.045       0   268.9     0.1       0
Bank Sta=250.4,268.9
XS Rating Curve= 0 ,0
Exp/Cntr(USF)=0,0
Exp/Cntr=0.3,0.1

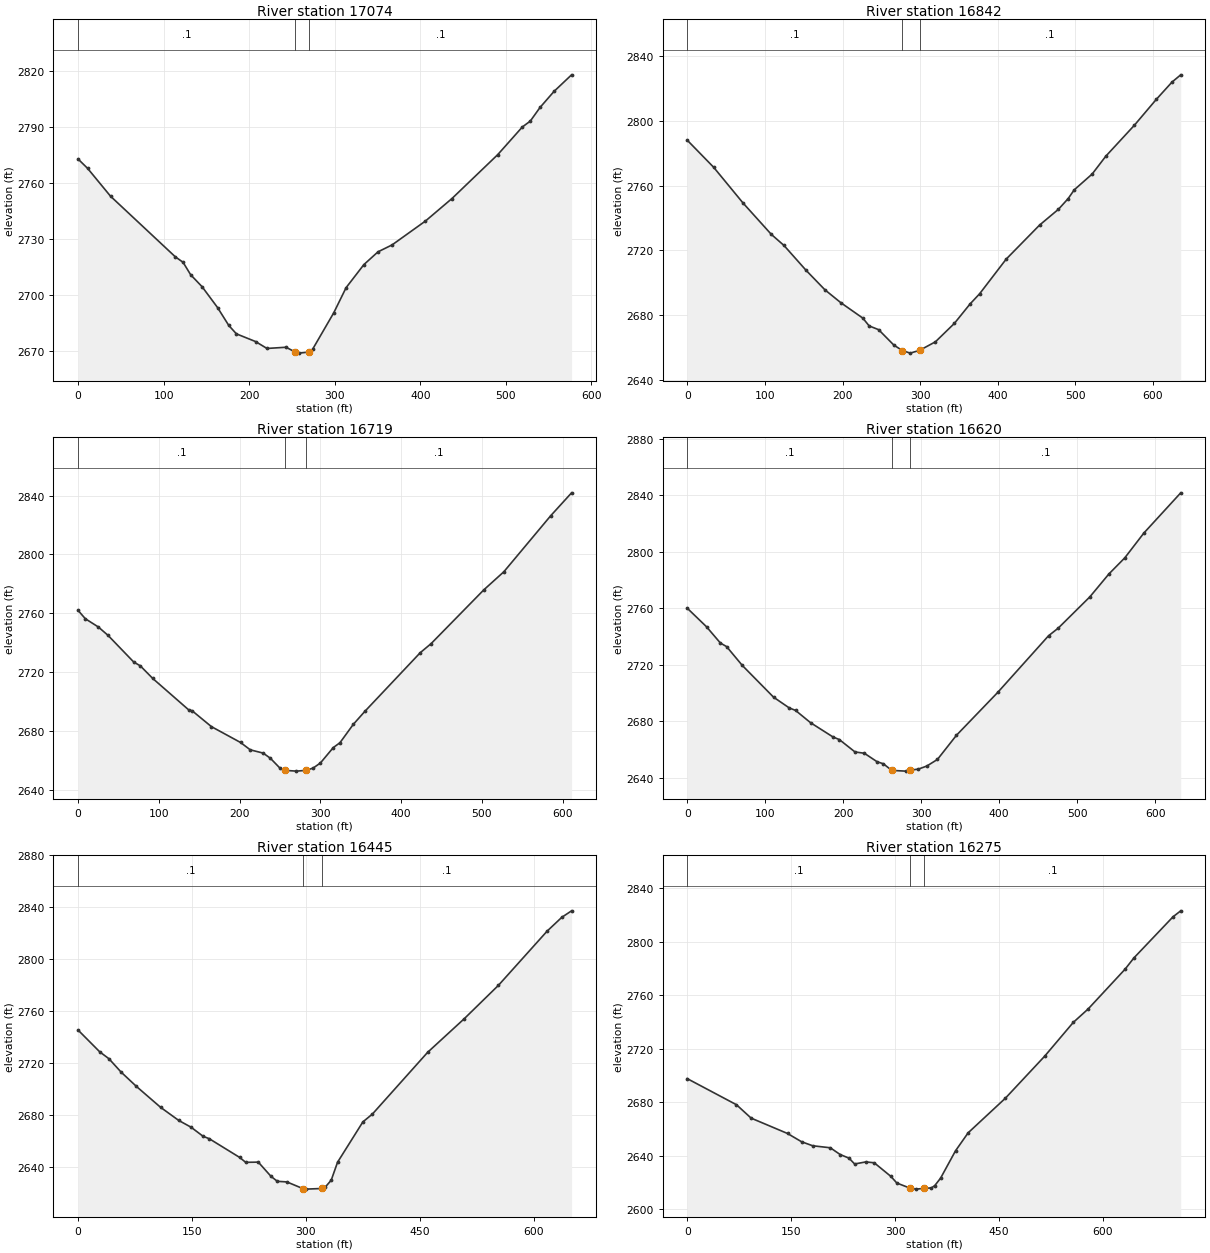
Type RM Length L Ch R = 1 ,17074   ,236,232.2,224
XS GIS Cut Line= 3
2338744.44022664715455.1866732562338610.49997305715726.591923946
2338545.64469236715993.062533714
#Sta/Elev= 30
       0 2772.83    11.1 2767.86    37.9 2752.97   113.7 2720.55   122.7 2717.66
   131.6 2710.98     145 2704.56     163 2693.47   176.2 2683.86   185.1 2679.39
   207.4 2675.29   220.8 2671.59   243.1 2672.23   253.7  2669.7   258.5 2669.09
   270.5  2669.7   274.3 2671.27   298.9 2690.66   313.3 2704.07   334.1 2716.41
   350.6 2723.23   367.1 2726.94   406.1  2739.7   437.1 2751.73   490.6 2775.19
   519.4 2789.99   528.6 2793.09     540 2800.38   556.4 2808.99   576.9 2817.84
#Mann= 3, -1 ,  0
       0     0.1       0   253.7   0.045       0   270.5     0.1       0
Bank Sta=253.7,270.5
XS Rating Curve= 0 ,0
Exp/Cntr(USF)=0,0
Exp/Cntr=0.3,0.1

Type RM Length L Ch R = 1 ,16842   ,124.6,123.6,122.4
XS GIS Cut Line= 2
2338364.93509661715366.5515106342338477.77564469715992.190082298
#Sta/Elev= 30
       0 2787.95      34 2771.27    71.8 2749.28   108.3 2729.91   124.6 2723.09
   153.1 2707.75   177.4 2695.73   197.9 2687.79   226.2  2678.3   234.3 2673.52
   246.5  2671.2   266.1 2661.71   277.1 2658.33   287.2 2656.74   299.4 2658.48
   319.7 2663.72   344.1 2675.06   364.4 2687.09   376.6  2693.3   410.8 2714.65
   453.8 2735.62   478.2  2745.4   490.6 2751.93   498.5 2757.36   521.6 2767.11
   539.2 2778.11   575.8 2797.07   604.2  2813.1   624.5 2823.79   635.7 2828.24
#Mann= 3, -1 ,  0
       0     0.1       0   277.1   0.045       0   299.4     0.1       0
Bank Sta=277.1,299.4
XS Rating Curve= 0 ,0
Exp/Cntr(USF)=0,0
Exp/Cntr=0.3,0.1

Type RM Length L Ch R = 1 ,16719   ,97.5,98.7,99.5
XS GIS Cut Line= 3
2338276.87340927715408.1984301632338286.67419913715643.417386875
2338384.68209776716006.046611807
#Sta/Elev= 30
       0 2761.88       9 2756.23      25 2750.65      37 2744.97      69 2726.73
      77 2724.23    92.5  2715.6   137.1  2694.2   141.1 2693.72   165.1 2682.87
   201.2 2672.09   213.2 2667.09   229.2 2664.87   238.1 2661.37   249.7 2654.81
   256.5 2653.11   270.4 2652.61   282.8 2653.15   291.1 2654.71   300.1 2658.16
     316 2668.61   324.3 2671.93   340.8 2684.41     355 2693.18   423.7 2733.14
   437.1 2739.28   502.4 2775.86   527.3 2788.21   585.3  2826.3   611.1 2841.85
#Mann= 3, -1 ,  0
       0     0.1       0   256.5   0.045       0   282.8     0.1       0
Bank Sta=256.5,282.8
XS Rating Curve= 0 ,0
Exp/Cntr(USF)=0,0
Exp/Cntr=0.3,0.1

Type RM Length L Ch R = 1 ,16620   ,176.7,174.5,174.5
XS GIS Cut Line= 3
 2338171.9164521715422.8245982782338190.94075932715652.289709865
2338266.97362685716047.607313198
#Sta/Elev= 30
       0 2760.07    24.7 2746.91    42.5 2735.38    50.5 2732.84    70.6  2719.5
   110.7    2697   130.8  2689.4   138.8 2687.66   158.1 2678.93     187 2668.78
     195 2666.98   215.1  2658.2   227.1 2657.27   243.4 2651.27   251.5 2649.81
   262.22645.139   279.9 2644.61     2862645.315   296.3 2646.02   307.2 2648.22
   320.8 2652.88   345.2 2670.02   398.2 2700.44   463.3 2740.55   475.6 2745.89
   516.3 2768.13   540.7 2784.35   561.1 2795.78   585.5 2813.32   632.8 2841.83
#Mann= 3, -1 ,  0
       0     0.1       0   262.2   0.045       0     286     0.1       0
Bank Sta=262.2,286
XS Rating Curve= 0 ,0
Exp/Cntr(USF)=0,0
Exp/Cntr=0.3,0.1

Type RM Length L Ch R = 1 ,16445   ,170.6,170.3,170.2
XS GIS Cut Line= 3
2338004.52530364715460.5816942082338014.28012353715682.837204541
2338136.66042769716092.574010382
#Sta/Elev= 30
       0 2745.39    28.6 2728.59    40.6 2723.36    56.7 2713.03    76.9 2701.98
   108.7 2685.92   132.7 2675.79   148.7 2670.67   164.8 2663.58   172.8 2661.77
   212.8 2647.38   220.8 2643.58   237.4 2643.75   254.1 2632.82   262.5 2628.97
     275 2628.52   295.9 2623.43   300.1 2622.96   320.9 2623.45   325.5 2624.41
   333.5 2629.89   341.8 2643.65   375.2 2674.73   387.7 2680.72   460.5 2728.27
   508.8 2754.18   553.8 2779.86     618 2821.62   637.3 2832.22   650.1 2837.18
#Mann= 3, -1 ,  0
       0     0.1       0   295.9   0.045       0   320.9     0.1       0
Bank Sta=295.9,320.9
XS Rating Curve= 0 ,0
Exp/Cntr(USF)=0,0
Exp/Cntr=0.3,0.1

Type RM Length L Ch R = 1 ,16275   ,350.5,348.7,346.9
XS GIS Cut Line= 4
2337823.80039908715481.7520998732337862.76703642715774.549608473
2337893.39450475715866.4320134392338076.80154254716128.514420889
#Sta/Elev= 30
       0 2697.51      71 2677.99    92.2 2667.96   144.7 2656.47   164.9 2650.31
     181 2647.29   206.4 2645.79   220.6 2640.75   233.5    2638   241.5 2633.67
   257.7 2635.21   269.8 2634.56     294  2624.3   302.4 2619.41   321.92615.493
   330.2 2614.85   341.32615.395   352.3 2615.77   357.2 2617.52   365.6  2623.1
   387.1 2643.52   405.3 2656.96   459.1 2682.89   515.7 2714.27     557 2739.56
   578.5 2749.63   631.7 2779.35   644.6 2787.86   701.1 2818.65   712.1 2823.05
#Mann= 3, -1 ,  0
       0     0.1       0   321.9   0.045       0   341.3     0.1       0
Bank Sta=321.9,341.3
XS Rating Curve= 0 ,0
Exp/Cntr(USF)=0,0
Exp/Cntr=0.3,0.1

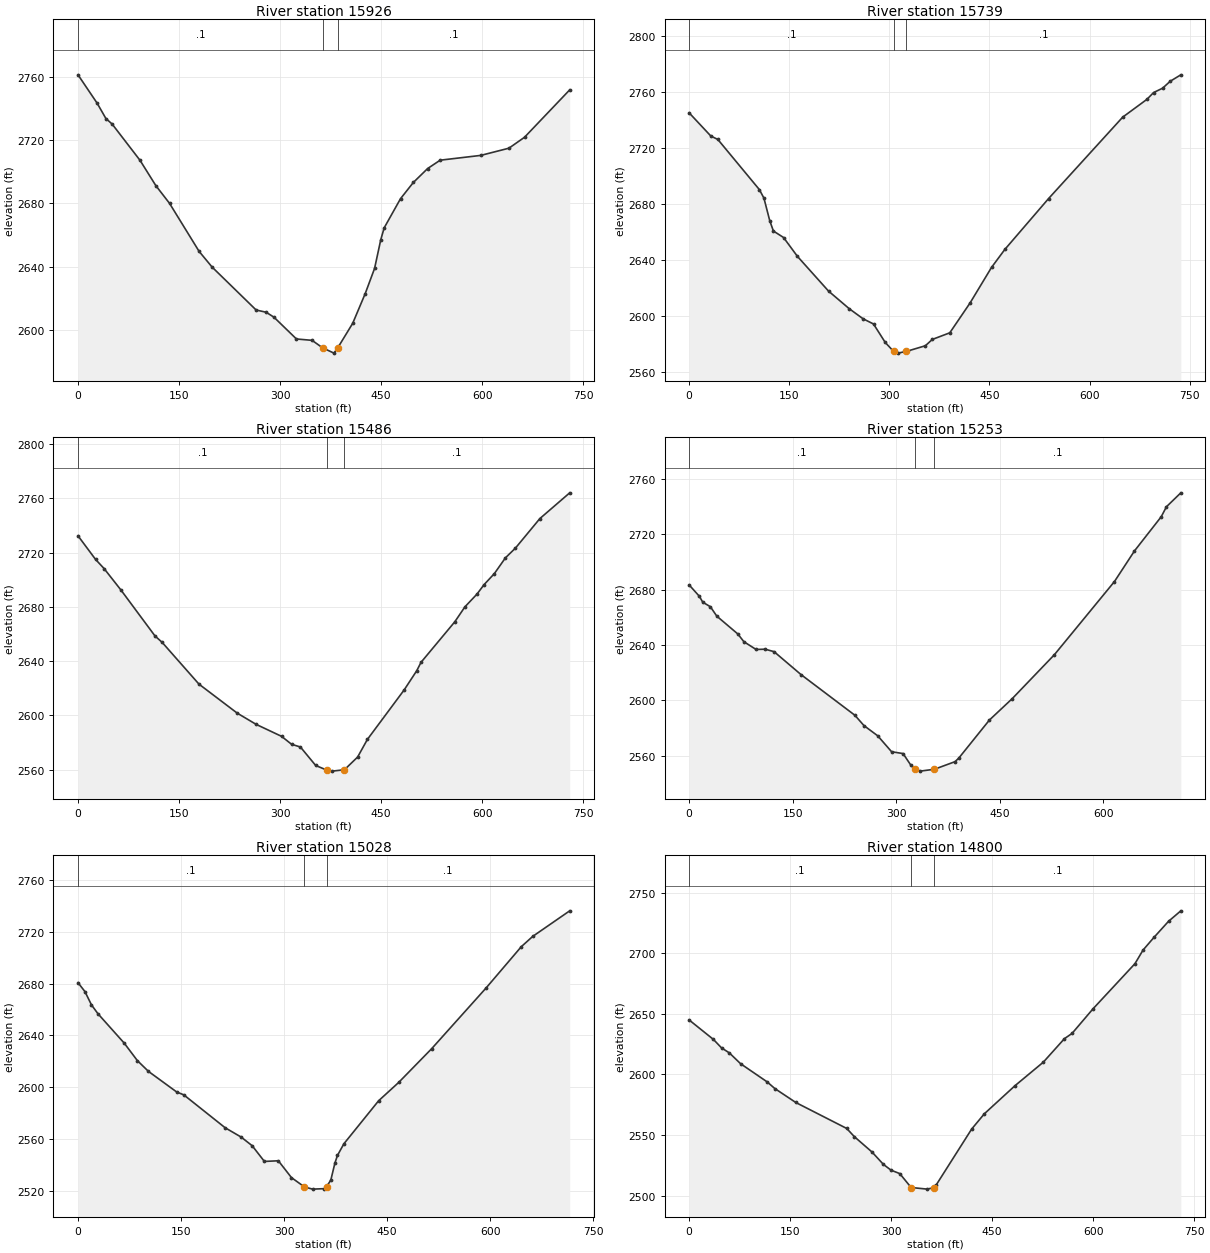
Type RM Length L Ch R = 1 ,15926   ,188.6,187.3,186.1
XS GIS Cut Line= 2
2337413.81003006715689.4812521522337783.33249635 716319.04709216
#Sta/Elev= 30
       0 2761.34    28.4  2743.4    41.4 2733.71    50.7 2730.19    92.1 2707.24
   115.6 2691.22   135.9 2680.03   179.8 2649.64   199.1 2639.71   264.5 2612.54
   279.2 2611.17   290.9 2608.02   324.3 2594.23   347.5 2593.37   363.1 2588.64
     380 2585.28   385.5 2588.55   407.8 2604.12   426.4 2622.94   440.3 2638.88
   449.5 2657.04   454.5  2664.5   478.8 2682.98   497.8 2693.23   519.1 2702.07
   537.7 2707.34     598 2710.37   639.7 2714.92   662.9 2721.84     730 2751.84
#Mann= 3, -1 ,  0
       0     0.1       0   363.1   0.045       0   385.5     0.1       0
Bank Sta=363.1,385.5
XS Rating Curve= 0 ,0
Exp/Cntr(USF)=0,0
Exp/Cntr=0.3,0.1

Type RM Length L Ch R = 1 ,15739   ,251.4,253.3,253.1
XS GIS Cut Line= 3
2337231.63292327715843.9510048652337479.31113303716144.529425801
2337694.49433846716417.187761954
#Sta/Elev= 30
       0 2744.97    32.5  2728.4    43.1 2725.91   105.3  2690.1   112.1 2684.01
   120.8 2667.95   126.3 2660.51   141.5 2655.89   162.3 2642.41   208.9 2617.61
   239.9 2605.04   260.7 2597.82   276.3 2594.11   293.9  2580.9   306.4 2574.52
   312.6 2573.29   325.2 2574.46     354 2578.56   364.4 2583.07   390.6  2587.8
   420.9 2609.06   453.2 2634.57   473.1 2647.37   538.6 2683.69   649.7 2741.87
   685.9 2754.55     696 2759.44   709.5 2762.55   720.9 2767.51   736.8  2772.1
#Mann= 3, -1 ,  0
       0     0.1       0   306.4   0.045       0   325.2     0.1       0
Bank Sta=306.4,325.2
XS Rating Curve= 0 ,0
Exp/Cntr(USF)=0,0
Exp/Cntr=0.3,0.1

Type RM Length L Ch R = 1 ,15486   ,225.2,233.1,237.1
XS GIS Cut Line= 2
2337035.50776368715988.9317476352337500.97758279716551.282036597
#Sta/Elev= 30
       0 2732.46    26.1 2715.02    38.7  2708.3    63.8 2692.43   114.3 2658.56
   124.9 2653.84   179.6    2623   236.4  2601.6   264.5 2593.31   302.2 2584.48
   317.1 2578.61   330.2 2576.61   352.9 2562.97     369 2559.65   377.4 2558.81
   395.5 2559.82   415.1 2569.18   429.6 2582.19   484.1 2618.65   502.9  2632.9
   509.2 2639.06   559.4 2669.01   574.5 2680.08   592.3 2689.42   602.9 2696.45
   618.2 2704.61   634.6 2716.22   649.4 2723.37   685.7 2745.18     730 2764.17
#Mann= 3, -1 ,  0
       0     0.1       0     369   0.045       0   395.5     0.1       0
Bank Sta=369,395.5
XS Rating Curve= 0 ,0
Exp/Cntr(USF)=0,0
Exp/Cntr=0.3,0.1

Type RM Length L Ch R = 1 ,15253   ,237.5,224.4,216.4
XS GIS Cut Line= 4
2336880.50280176716101.5709114662337059.36721676716330.664374514
2337082.64409269716418.871483281  2337310.512457716657.765736191
#Sta/Elev= 30
       0 2683.52    14.7 2675.37    19.8 2671.02    30.8 2667.74    40.1 2660.94
    70.5 2648.07    79.3 2642.46      97 2636.84     110 2637.05     123 2635.27
   161.9 2618.75     240 2589.31   253.2 2581.82   273.1 2574.44   293.2 2562.92
   309.8 2561.61   321.1 2553.19   326.8 2550.39   334.6 2548.91   355.3 2550.27
   385.1 2555.77   390.6 2558.39   434.8 2585.83     468 2601.37   528.9 2633.06
   615.9 2685.96   644.9  2708.1   683.6 2732.79   691.2 2740.03     712 2750.08
#Mann= 3, -1 ,  0
       0     0.1       0   326.8   0.045       0   355.3     0.1       0
Bank Sta=326.8,355.3
XS Rating Curve= 0 ,0
Exp/Cntr(USF)=0,0
Exp/Cntr=0.3,0.1

Type RM Length L Ch R = 1 ,15028   ,225.3,228,232.2
XS GIS Cut Line= 3
2336643.74724388716353.1847102812336963.88321512716561.568150484
2337198.02045189716799.406913235
#Sta/Elev= 30
       0 2680.67    10.1  2673.8    19.6 2663.56    29.1 2656.71    67.3  2634.1
    86.4 2620.67   102.6 2612.34   143.7 2596.48     154 2594.29   214.2 2568.95
   237.4 2561.81   253.5 2555.14   271.3 2543.03   291.6 2543.54   310.7 2530.58
   329.6  2523.4   341.4 2521.71   358.5 2522.07   361.7 2523.49     368 2528.72
   373.9  2541.7   377.6 2547.61     387 2556.62   437.6 2589.77   466.8 2603.87
   514.9 2629.91   594.1 2676.65   645.2 2708.35   661.9 2716.31   715.7 2735.98
#Mann= 3, -1 ,  0
       0     0.1       0   329.6   0.045       0   361.7     0.1       0
Bank Sta=329.6,361.7
XS Rating Curve= 0 ,0
Exp/Cntr(USF)=0,0
Exp/Cntr=0.3,0.1

Type RM Length L Ch R = 1 ,14800   ,181.3,185.3,185.8
XS GIS Cut Line= 2
2336530.71995438716458.6303736672337043.58971879716978.115315457
#Sta/Elev= 30
       0 2644.98    36.2 2628.84    48.1 2621.93    59.8 2617.75    76.4 2608.86
   115.9 2593.84   127.2 2588.38   158.4 2576.84     234 2555.41   245.3 2548.65
   271.5 2535.98   288.5 2525.73   299.8 2520.98   312.7 2518.17   329.6 2506.68
   353.6 2505.34   363.3 2506.66   366.5 2508.51   419.5 2554.94   438.4 2567.58
   483.7 2590.66   525.9 2610.15   557.2 2629.54   568.5 2633.85   599.6 2654.14
   661.9 2691.42   673.9 2702.65   690.2 2713.16   711.8 2726.42     730 2735.04
#Mann= 3, -1 ,  0
       0     0.1       0   329.6   0.045       0   363.3     0.1       0
Bank Sta=329.6,363.3
XS Rating Curve= 0 ,0
Exp/Cntr(USF)=0,0
Exp/Cntr=0.3,0.1

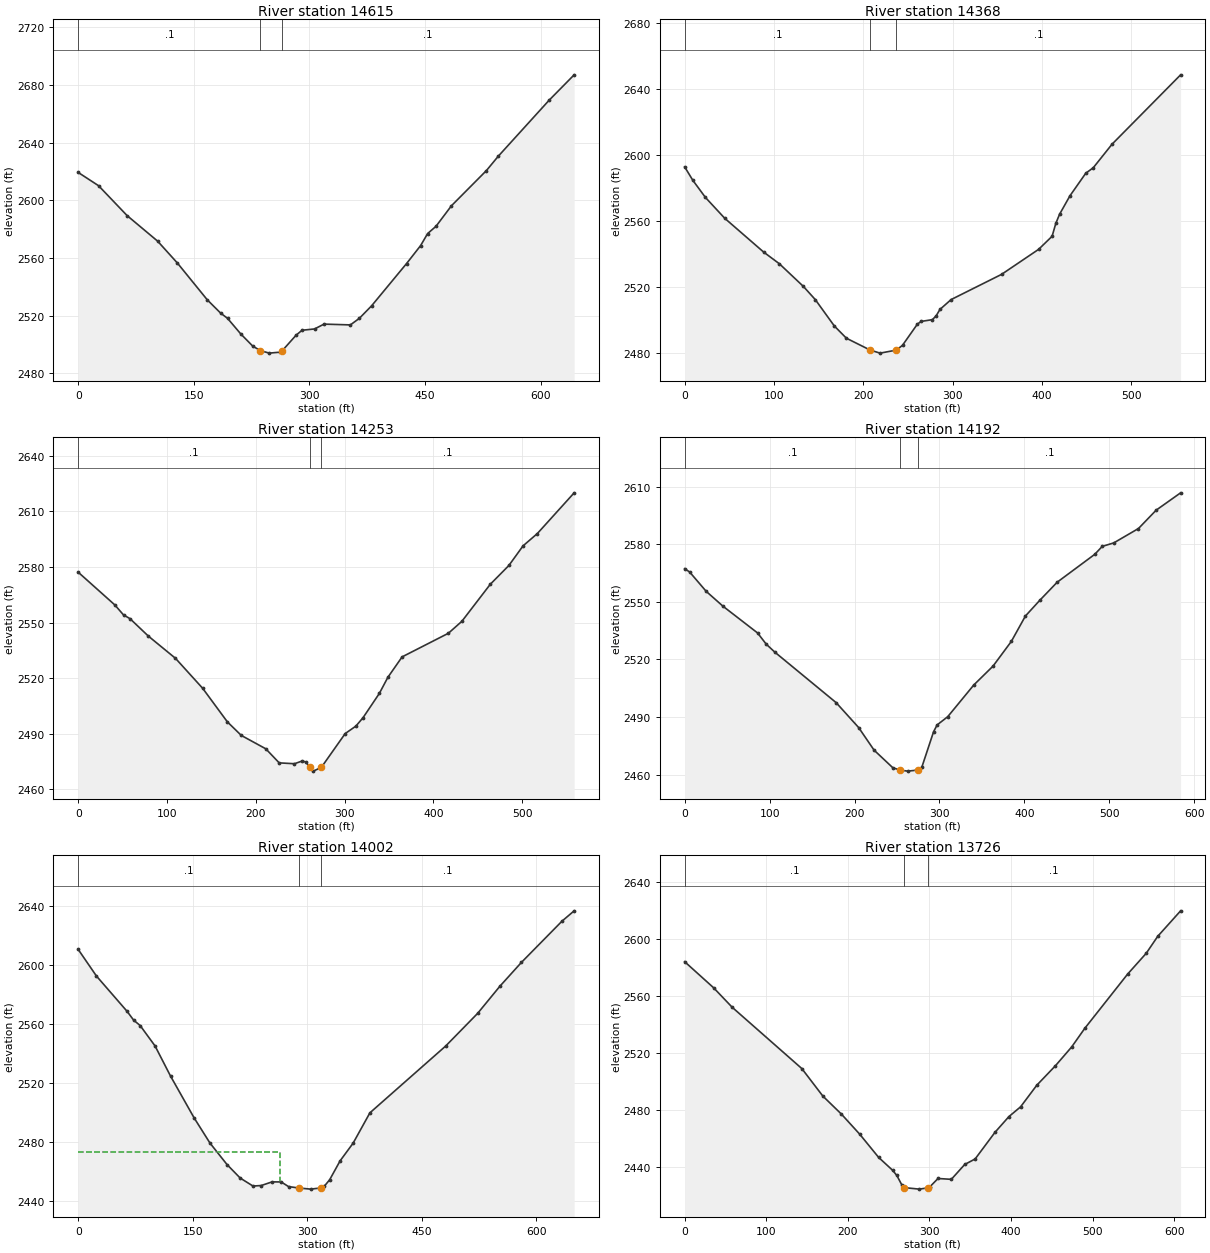
Type RM Length L Ch R = 1 ,14615   ,253,246.5,235.5
XS GIS Cut Line= 4
2336455.10341362 716608.974076122336597.56017165716774.910665034
 2336695.0305069716898.1241942072336905.76787636717063.428829894
#Sta/Elev= 30
       0  2619.4    26.4 2610.21    63.5 2589.46     103  2571.8   128.6 2556.66
   167.4 2531.14   184.8 2521.88   193.8 2518.24   211.1 2507.34   226.7 2498.88
   236.4 2495.92   247.8 2494.12     262 2494.79   264.9 2495.88   282.8 2506.58
   290.5 2509.99   306.7 2510.88     319 2514.24   353.2 2513.69   364.8 2518.22
   380.8 2526.96   426.1 2556.22   444.3 2568.65   453.5 2577.05   464.3 2582.05
   484.4 2596.32   529.8 2620.74     545 2630.57   611.1 2669.47   643.6 2687.09
#Mann= 3, -1 ,  0
       0     0.1       0   236.4   0.045       0   264.9     0.1       0
Bank Sta=236.4,264.9
XS Rating Curve= 0 ,0
Exp/Cntr(USF)=0,0
Exp/Cntr=0.3,0.1

Type RM Length L Ch R = 1 ,14368   ,116.8,115.5,113.4
XS GIS Cut Line= 3
 2336346.0623999716850.5009055882336465.93484879716983.052171186
2336825.55219546717094.856282169
#Sta/Elev= 30
       0  2592.6     9.1 2584.49    23.2 2574.12    44.9 2561.45    88.4 2541.03
   106.1 2533.91     133 2520.18   146.3 2512.21   167.6 2496.25   181.1 2488.86
   207.8 2481.66   218.8 2479.84   237.12481.684   243.9 2484.59   260.6 2497.42
   264.8 2499.04   277.4 2500.11   281.6 2502.44   285.8 2506.28   298.3 2512.26
   354.8 2527.52   396.3 2542.67   411.4 2550.59   415.6 2558.46   419.8 2563.95
   431.4  2575.1   449.1 2588.76   457.5 2592.08   478.5 2606.32   555.3 2648.33
#Mann= 3, -1 ,  0
       0     0.1       0   207.8   0.045       0   237.1     0.1       0
Bank Sta=207.8,237.1
XS Rating Curve= 0 ,0
Exp/Cntr(USF)=0,0
Exp/Cntr=0.3,0.1

Type RM Length L Ch R = 1 ,14253   ,57,60.4,63.5
XS GIS Cut Line= 3
2336265.84058657716945.7302110712336466.96245156  717103.0747616
 2336769.5969298 717118.93610742
#Sta/Elev= 30
       0 2577.12    41.2 2559.49      51  2554.1    58.3 2552.08    79.1 2542.62
   109.5  2530.7   140.1 2514.54   167.9 2496.45   183.6 2489.12   211.2  2481.9
   226.3 2474.31   243.5 2473.85   252.3 2475.34   256.6 2474.72   260.6 2471.82
   264.6 2469.86   273.7 2471.84   300.6 2490.11   312.6 2494.12   320.7 2498.67
     339 2511.72   348.7 2520.48   364.7 2531.47   416.8  2544.2     432 2550.66
     464 2570.63   484.9 2580.75   500.9 2591.35   516.9 2597.94   558.4 2619.93
#Mann= 3, -1 ,  0
       0     0.1       0   260.6   0.045       0   273.7     0.1       0
Bank Sta=260.6,273.7
XS Rating Curve= 0 ,0
Exp/Cntr(USF)=0,0
Exp/Cntr=0.3,0.1

Type RM Length L Ch R = 1 ,14192   ,187.8,190.7,200.1
XS GIS Cut Line= 4
2336252.11876431716985.430944489 2336371.9912132717107.608632779
2336473.42174687717169.8500966252336755.81357358717250.533475685
#Sta/Elev= 30
       0 2567.31     5.8  2565.6    25.3 2555.52    45.1 2547.75    85.8 2533.83
      96 2527.99   106.1 2523.84   178.3 2497.52   204.8 2484.54     223 2472.75
   245.1 2463.56   253.9 2462.35   262.6 2461.82   274.6 2462.37   279.3 2463.99
     293 2482.29   297.2 2485.89   309.7 2490.18   340.4 2506.71     363 2516.52
   384.6 2529.42   401.2 2542.66     418 2550.79   438.6 2560.28   482.8 2574.79
   491.6 2578.92   505.2 2580.75   534.3 2588.25   555.1  2597.8   583.9 2606.84
#Mann= 3, -1 ,  0
       0     0.1       0   253.9   0.045       0   274.6     0.1       0
Bank Sta=253.9,274.6
XS Rating Curve= 0 ,0
Exp/Cntr(USF)=0,0
Exp/Cntr=0.3,0.1

Type RM Length L Ch R = 1 ,14002   ,277.3,275.5,271.8
XS GIS Cut Line= 4
2336120.93294196717018.4917505982336251.54758443717182.455379433
2336309.96394427717298.1889025762336523.06359035 717523.32539859
#Sta/Elev= 30
       0 2610.69    23.9 2592.62      64 2568.67    72.5 2562.74    81.1 2559.02
   100.6 2545.18   120.9  2524.7   151.7 2496.39   172.5 2479.25   194.9 2464.62
   212.1 2455.49   228.8 2450.08   239.6 2450.42   253.8  2452.9   265.7 2452.86
   275.4  2449.7   288.9 2448.74   304.4 2447.98   317.5 2448.78   322.3 2450.02
   329.2 2454.34   342.9  2467.2   359.9 2479.18   381.9 2499.78   481.1 2545.13
   522.9 2567.27   552.3 2585.85   580.2 2601.86   633.4  2629.9   649.3 2636.91
#Mann= 3, -1 ,  0
       0     0.1       0   288.9   0.045       0   317.5     0.1       0
#XS Ineff= 2 , 0
          263.83 2473.28
Permanent Ineff=
       F       F
Bank Sta=288.9,317.5
XS Rating Curve= 0 ,0
Exp/Cntr(USF)=0,0
Exp/Cntr=0.3,0.1

Type RM Length L Ch R = 1 ,13726   ,324.3,330.1,330.7
XS GIS Cut Line= 2
2335908.42952026717211.3271717442336279.98615446717692.645207932
#Sta/Elev= 30
       0 2584.38    35.4 2566.11    58.2 2552.41   143.6 2509.38   169.4 2490.05
   192.2 2477.37   214.6 2463.29   237.8    2447   254.9 2437.98   260.1 2434.32
   266.4 2427.47   269.2  2425.8   287.6 2424.74   297.7  2425.6   300.6 2426.39
   310.6 2432.21   326.9 2431.61   343.3 2442.04   356.1 2445.92   380.4  2464.6
   397.5 2475.66   411.8  2482.5   431.6 2497.62   454.6 2511.39   474.5 2524.59
   490.5  2537.6     543 2575.66   565.8 2590.26     580 2602.24     608 2620.09
#Mann= 3, -1 ,  0
       0     0.1       0   269.2   0.045       0   297.7     0.1       0
Bank Sta=269.2,297.7
XS Rating Curve= 0 ,0
Exp/Cntr(USF)=0,0
Exp/Cntr=0.3,0.1