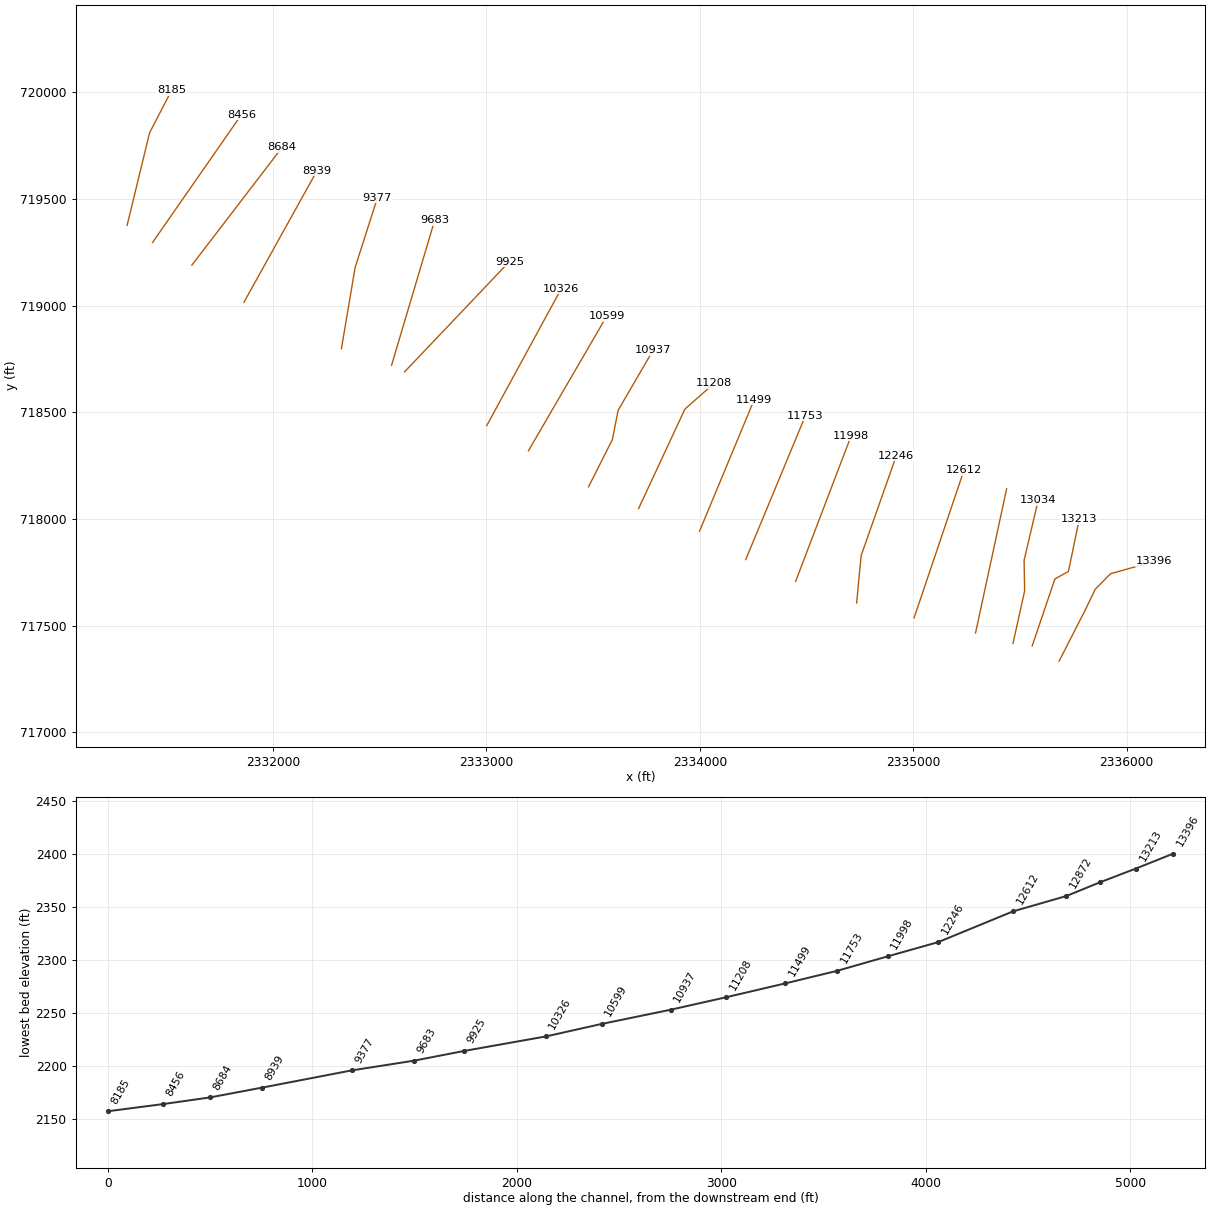
HEC-RAS study LTBLACKFK.prj: LTBLACKFK

--- LTBLACKFK.g01 (geometry) --- (continued)

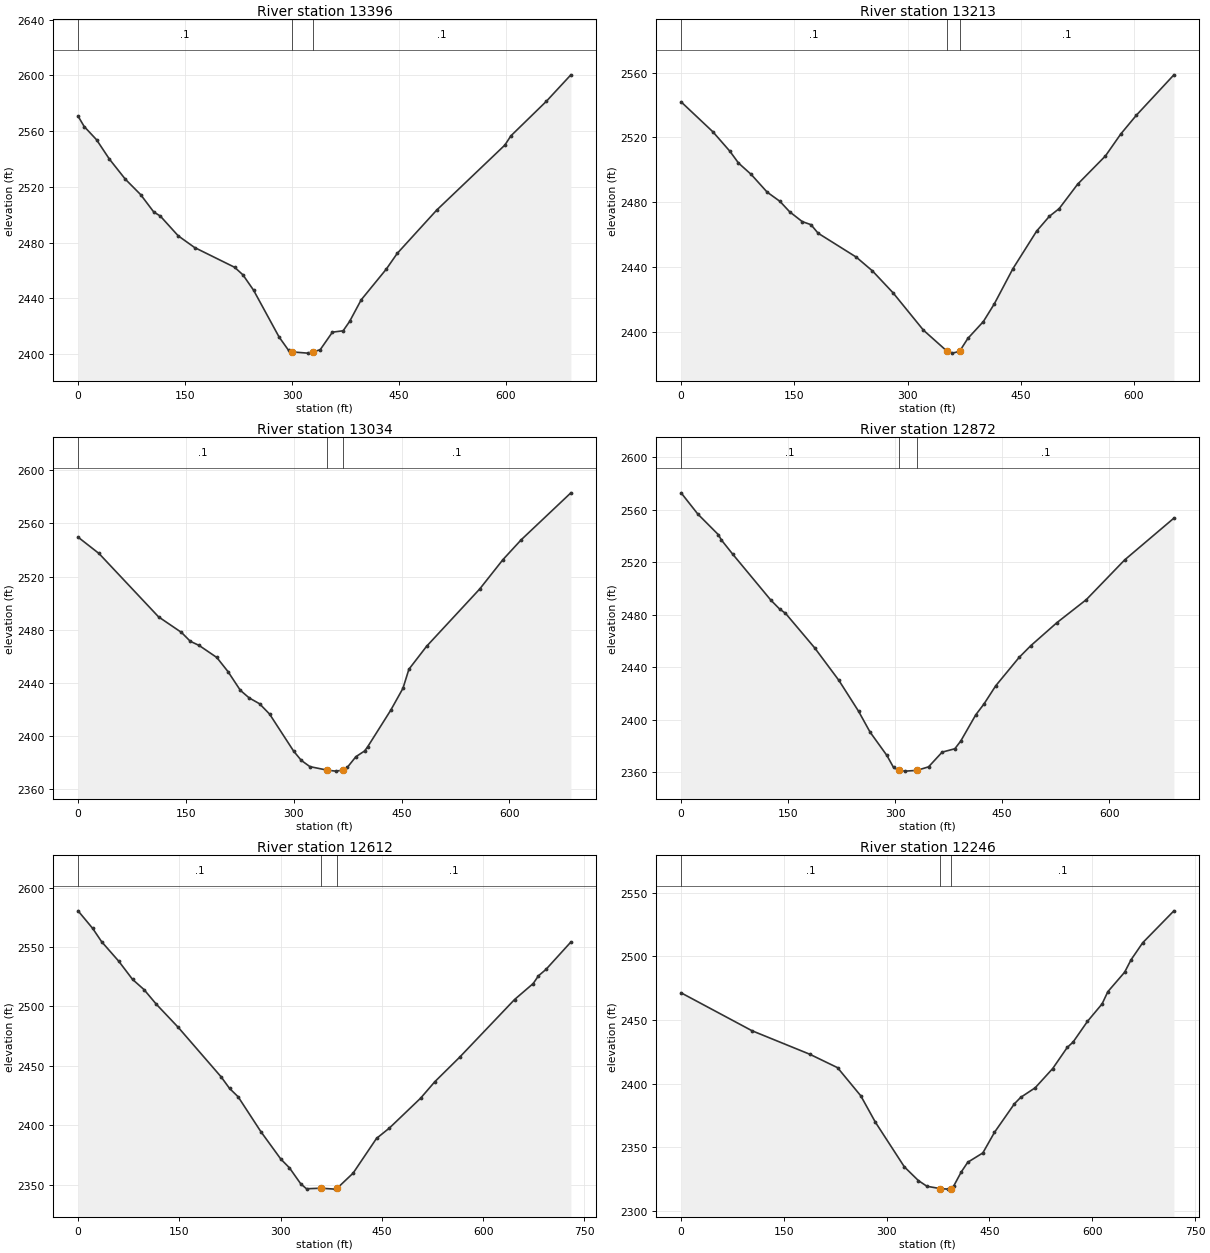
Type RM Length L Ch R = 1 ,13396   ,191.2,183.3,177.2
XS GIS Cut Line= 5
2335684.24784474717334.1535978512335808.27646139717576.669844533
2335853.60511451717671.0024469652335924.66084101717743.283272204
2336129.19385871717800.891204962
#Sta/Elev= 30
       0 2570.77     8.6 2563.31    25.9 2553.85    43.8 2540.04    66.3 2525.51
    87.7 2514.49   106.2 2501.95   115.2 2499.14   140.4  2484.9   163.4  2476.5
   219.5 2462.33   231.1 2456.93     246 2445.94   281.8 2412.34   295.1 2402.77
   299.3 2401.65   321.8 2400.75   329.6 2401.61   339.5 2403.22   356.6  2415.8
   371.6 2416.77   380.7 2423.49   396.9 2438.96   432.1 2461.01   447.4 2472.26
   502.8 2503.37   598.4 2550.03   606.7 2556.57   656.6 2581.45   690.9  2600.4
#Mann= 3, -1 ,  0
       0     0.1       0   299.3   0.045       0   329.6     0.1       0
Bank Sta=299.3,329.6
XS Rating Curve= 0 ,0
Exp/Cntr(USF)=0,0
Exp/Cntr=0.3,0.1

Type RM Length L Ch R = 1 ,13213   ,168.8,178.3,187
XS GIS Cut Line= 4
2335557.97020564717405.1876104252335664.40310882717718.884588209
2335727.88940194717754.3622226012335778.30498766717998.037553558
#Sta/Elev= 30
       0 2541.88    42.2 2523.34    64.8 2511.27      76  2504.1    92.9 2497.02
     114  2486.1   130.9 2480.43   143.8 2473.96   160.5 2467.89     172 2466.01
   181.5 2460.73     232 2445.97   253.4 2437.47   280.8 2423.89     321 2400.83
   352.4 2387.78   359.2 2386.64   368.8  2387.7   379.8  2395.7   400.4 2406.15
     415 2417.16   439.5 2438.79   470.9 2461.99   487.8 2471.16   500.8 2475.92
   525.3 2491.03   562.1 2508.47   582.5 2522.08   602.9 2533.53   652.8 2558.58
#Mann= 3, -1 ,  0
       0     0.1       0   352.4   0.045       0   368.8     0.1       0
Bank Sta=352.4,368.8
XS Rating Curve= 0 ,0
Exp/Cntr(USF)=0,0
Exp/Cntr=0.3,0.1

Type RM Length L Ch R = 1 ,13034   ,164.5,162.1,158.9
XS GIS Cut Line= 4
2335467.99092997717416.7651765412335522.46434406717663.187284281
 2335520.0141466717806.523836028 2335586.2813312718088.470654319
#Sta/Elev= 30
       0 2549.66    29.1 2537.35     112 2489.61   143.8 2477.92   156.1 2471.23
   168.4 2468.09     193 2459.02   208.5 2448.42   225.7 2434.31     238 2428.58
   252.4  2424.2   266.4 2416.39   299.8 2388.53   310.4 2381.58   322.4 2376.85
   346.4 2374.19   358.4 2373.45   368.7  2374.2   374.4 2376.23   386.4 2384.31
   398.5 2388.63   402.6 2391.63   434.7 2419.18   451.9 2435.86   460.1 2450.15
   484.7 2467.44   558.7 2510.67     591 2532.78   616.2 2547.61   685.4 2583.03
#Mann= 3, -1 ,  0
       0     0.1       0   346.4   0.045       0   368.7     0.1       0
Bank Sta=346.4,368.7
XS Rating Curve= 0 ,0
Exp/Cntr(USF)=0,0
Exp/Cntr=0.3,0.1

Type RM Length L Ch R = 1 ,12872   ,263,260.8,260
XS GIS Cut Line= 2
2335292.44240772717466.183649658 2335438.0646554718141.224384485
#Sta/Elev= 30
       0    2573    23.5 2556.77    52.2 2541.09    56.3 2537.15    72.6 2526.03
   125.8 2491.12   138.1 2484.34   146.3 2481.09   187.2 2454.71   221.1 2429.94
   248.6 2406.45   264.8 2390.47   288.4 2372.64   297.7 2363.48   305.2 2361.27
   314.1 2360.69   330.4 2361.25   346.8 2363.96   365.8 2375.17   383.6 2377.76
   391.8 2383.58   412.9 2403.62   424.5 2411.97   440.9 2425.79   473.6 2447.39
     490 2456.37   526.8 2474.03   567.8  2491.5   621.6 2521.83   690.6  2553.7
#Mann= 3, -1 ,  0
       0     0.1       0   305.2   0.045       0   330.4     0.1       0
Bank Sta=305.2,330.4
XS Rating Curve= 0 ,0
Exp/Cntr(USF)=0,0
Exp/Cntr=0.3,0.1

Type RM Length L Ch R = 1 ,12612   ,364.3,366,365
XS GIS Cut Line= 2
2335004.37096955 717536.587503232335238.03755775  718228.1798149
#Sta/Elev= 30
       0 2580.42    21.7 2565.59      35 2554.37    60.3    2538    80.8 2522.66
    97.7 2514.14     116 2501.78   148.4 2482.36   211.8 2440.77   224.4 2430.97
   237.1 2423.94   270.8 2394.58   300.4 2371.45   313.1 2364.16     330 2350.56
   338.4 2346.52   359.5 2346.98   380.6 2346.21   383.9 2347.01   407.4 2359.65
   442.1  2388.9   461.1 2397.57   507.3 2422.69   528.4 2436.57   565.2 2457.21
   646.6 2505.78   674.2 2519.24     682 2525.75   693.1 2531.11     730 2554.17
#Mann= 3, -1 ,  0
       0     0.1       0   359.5   0.045       0   383.9     0.1       0
Bank Sta=359.5,383.9
XS Rating Curve= 0 ,0
Exp/Cntr(USF)=0,0
Exp/Cntr=0.3,0.1

Type RM Length L Ch R = 1 ,12246   ,247.7,247.3,247.2
XS GIS Cut Line= 3
2334735.05750988 717606.163103282334756.18314664 717828.58523326
 2334920.9774971718296.022192764
#Sta/Elev= 30
       0 2471.44   103.5 2441.64   187.9 2423.15   228.3 2412.63   262.2 2390.52
   283.4 2369.88   325.8 2334.68   346.2 2323.95   358.7 2319.45   377.5 2317.67
   389.5  2317.2   393.7 2317.53   397.9 2319.77   408.9 2330.79   418.3 2338.32
   440.3 2345.65   457.3 2361.84   486.4 2384.28   495.5 2389.29   516.7 2396.84
   542.2 2411.93   563.4  2428.5     572 2432.77     593 2449.05   614.3 2462.74
   622.7 2472.36   647.2 2487.65   656.6 2497.45   673.6 2510.82   719.1 2535.87
#Mann= 3, -1 ,  0
       0     0.1       0   377.5   0.045       0   393.7     0.1       0
Bank Sta=377.5,393.7
XS Rating Curve= 0 ,0
Exp/Cntr(USF)=0,0
Exp/Cntr=0.3,0.1

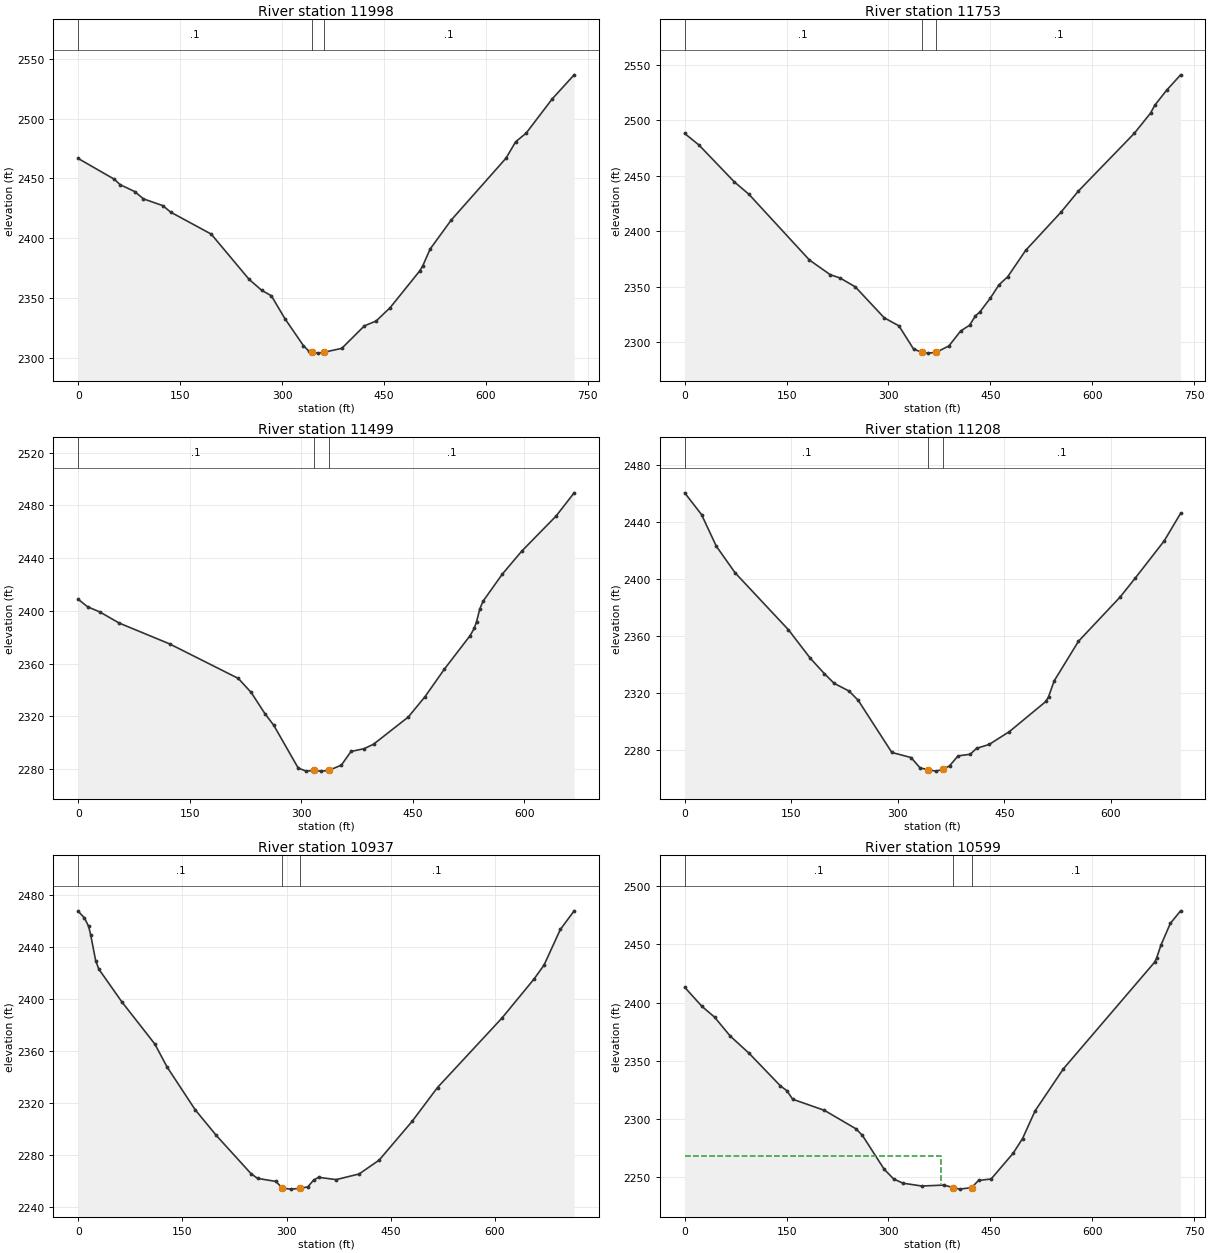
Type RM Length L Ch R = 1 ,11998   ,245.4,245.1,245.2
XS GIS Cut Line= 2
2334449.15875137 717707.510401682334709.38193791718389.554310228
#Sta/Elev= 30
       0 2466.68    53.2 2449.29    61.7 2444.77    83.1 2439.01      96 2432.88
   124.5 2427.22   136.1 2421.78   195.8 2403.38   251.5 2365.53   270.1 2356.34
   284.3 2351.77   304.2 2332.67   331.4 2310.12     340 2305.14   344.5 2304.51
   352.8 2303.76   361.4 2304.46   387.9 2307.74   421.3 2326.62   438.5 2330.63
   459.2 2341.86   502.6 2372.52     507  2376.6     518 2390.88     549 2415.11
   629.6 2466.87     644 2480.74   659.3 2487.86   697.8 2516.61     730  2536.7
#Mann= 3, -1 ,  0
       0     0.1       0   344.5   0.045       0   361.4     0.1       0
Bank Sta=344.5,361.4
XS Rating Curve= 0 ,0
Exp/Cntr(USF)=0,0
Exp/Cntr=0.3,0.1

Type RM Length L Ch R = 1 ,11753   ,253.7,254.5,253.8
XS GIS Cut Line= 2
2334215.39508322717809.8666871172334495.10396491718484.153674612
#Sta/Elev= 30
       0    2488    20.9 2477.69    72.9 2444.53    94.5 2433.28   183.7 2374.02
   214.3 2360.84   228.8 2357.86   251.1 2349.92   293.7 2322.05   315.4 2314.77
     337 2293.82     349 2291.08   358.7 2290.22   370.4 2290.98     389 2296.74
   406.3  2310.2   419.3 2315.32     428 2323.75   434.7 2327.45     450 2339.81
   462.6 2351.69   475.6  2359.1     502 2382.81   553.6 2416.92   579.5 2436.14
   661.8 2488.11   685.7 2506.31   692.1 2513.53   709.5    2527     730 2540.81
#Mann= 3, -1 ,  0
       0     0.1       0     349   0.045       0   370.4     0.1       0
Bank Sta=349,370.4
XS Rating Curve= 0 ,0
Exp/Cntr(USF)=0,0
Exp/Cntr=0.3,0.1

Type RM Length L Ch R = 1 ,11499   ,291,290.6,290.2
XS GIS Cut Line= 2
2333998.52968187717942.1851072942334254.71860186718558.408556962
#Sta/Elev= 30
       0 2408.78    12.7 2403.07    29.2 2399.15    55.2 2390.72   122.9 2374.94
   215.5 2348.69   232.8 2338.03   251.4 2321.85   263.2 2313.09     296 2280.71
   306.5 2278.34   316.9 2278.81   327.3 2278.32   337.1 2278.85   354.1 2282.86
   367.1 2293.24   384.5 2295.32   397.4 2298.73   444.2 2319.41   466.8 2334.93
   492.7 2355.72   527.4 2381.21   532.9 2386.68   536.1 2391.86   540.4 2401.41
   544.7 2407.24   570.7 2427.88   596.7 2445.24   643.1    2472   667.4 2489.61
#Mann= 3, -1 ,  0
       0     0.1       0   316.9   0.045       0   337.1     0.1       0
Bank Sta=316.9,337.1
XS Rating Curve= 0 ,0
Exp/Cntr(USF)=0,0
Exp/Cntr=0.3,0.1

Type RM Length L Ch R = 1 ,11208   ,268,270.7,272.9
XS GIS Cut Line= 3
2333713.04439829718048.7997733912333930.37585262718515.245510699
2334068.14006298718636.434362977
#Sta/Elev= 30
       0 2460.51    23.7 2445.26    44.5 2423.08      71 2404.38     146 2364.43
   176.9 2344.36   196.8 2333.51   210.4 2326.81   231.4 2321.37   244.2 2314.92
   291.6  2278.3   318.7  2274.7   331.4 2267.39   343.12266.217   353.4 2265.18
   363.82266.399   372.9 2268.95   384.9 2275.88     402 2277.04   410.8 2281.17
   428.5 2283.87   457.2 2292.97   508.4 2314.07   512.3 2317.52   520.1 2328.49
   554.3 2356.31   612.9 2387.36   634.2 2400.64     675 2426.79   698.1 2446.14
#Mann= 3, -1 ,  0
       0     0.1       0   343.1   0.045       0   363.8     0.1       0
Bank Sta=343.1,363.8
XS Rating Curve= 0 ,0
Exp/Cntr(USF)=0,0
Exp/Cntr=0.3,0.1

Type RM Length L Ch R = 1 ,10937   ,340.2,338.2,333.2
XS GIS Cut Line= 4
2333478.52578351718150.7611028822333590.07064905718371.561091411
2333617.29506533718509.1956404132333781.33720214718791.166160339
#Sta/Elev= 30
       0 2467.45       9  2462.3    14.9 2455.89    17.9 2449.45    25.1 2429.47
    29.6 2422.93    62.6 2397.82   110.3 2365.19   127.8 2347.61   168.5 2314.48
   198.8 2294.78     249 2265.21   258.2 2261.72   284.6 2259.36   293.9 2254.16
   306.1 2253.44   318.6 2253.96   330.6 2255.24   338.7 2260.31   345.9 2262.55
   371.4 2260.77   404.4 2265.13   433.2 2275.79   480.5 2305.55   517.2  2331.7
   609.8 2385.08   656.1  2415.2   670.6 2426.03     694 2453.41   713.9 2467.76
#Mann= 3, -1 ,  0
       0     0.1       0   293.9   0.045       0   318.6     0.1       0
Bank Sta=293.9,318.6
XS Rating Curve= 0 ,0
Exp/Cntr(USF)=0,0
Exp/Cntr=0.3,0.1

Type RM Length L Ch R = 1 ,10599   ,268.1,272.7,268.9
XS GIS Cut Line= 2
2333196.64636937 718319.263670182333563.61767001718950.319978687
#Sta/Elev= 30
       0 2413.28    25.4 2396.89    43.9 2387.69      67 2371.41    94.8 2356.61
     141 2328.57   150.3 2324.56     159 2317.17   205.8 2307.59   252.1 2291.79
   261.6 2286.13   293.7 2257.03   307.6 2248.73   321.5 2245.07   349.2 2242.66
   381.4 2243.48   395.5 2241.29   404.8    2240   422.4 2241.31   432.5 2247.43
   451.1 2248.71   483.4 2270.75   497.3 2283.38   515.8 2307.22   557.5 2343.31
   691.7 2434.78   694.5 2437.99   700.9 2449.24   714.9 2468.16     730 2478.88
#Mann= 3, -1 ,  0
       0     0.1       0   395.5   0.045       0   422.4     0.1       0
#XS Ineff= 2 , 0
          377.76 2268.79
Permanent Ineff=
       F       F
Bank Sta=395.5,422.4
XS Rating Curve= 0 ,0
Exp/Cntr(USF)=0,0
Exp/Cntr=0.3,0.1

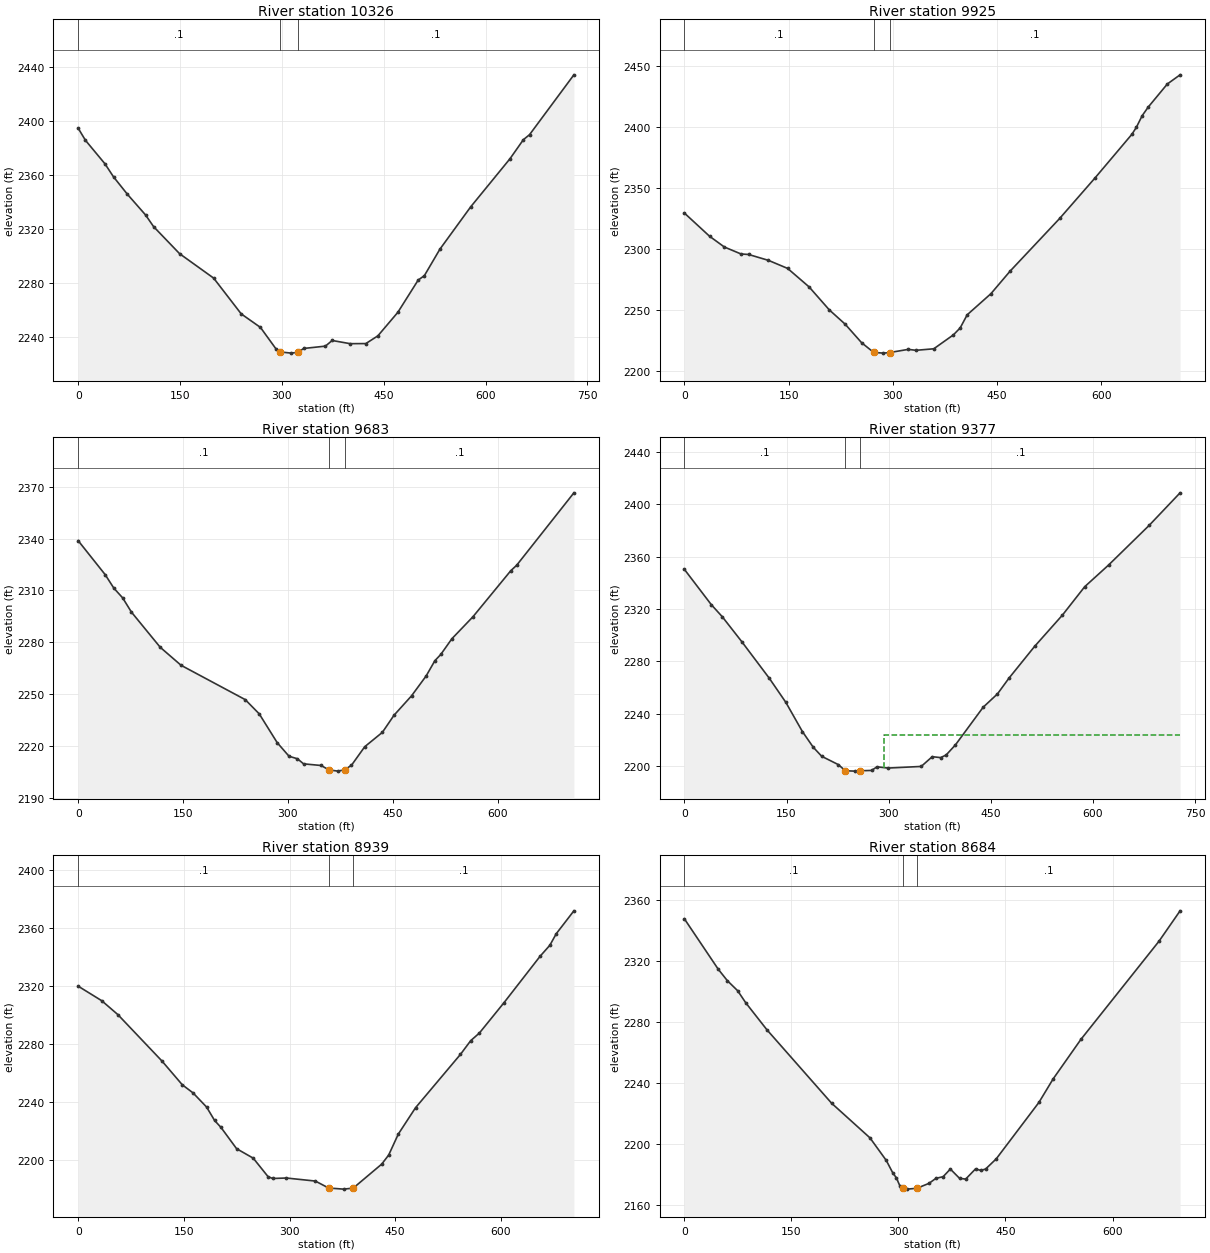
Type RM Length L Ch R = 1 ,10326   ,404.4,401.8,398.1
XS GIS Cut Line= 2
2333001.35287454718437.4303569972333350.42952437719078.558653476
#Sta/Elev= 30
       0 2394.75    10.7 2385.81    39.4 2368.43      52 2358.77    72.6 2345.78
    99.2 2330.55     111 2321.92   149.3 2301.87   199.5 2283.76   240.1 2257.27
   268.4 2247.26   291.2 2231.41   296.8 2229.13     314 2228.22   323.8 2228.91
   332.1 2231.68   364.1  2233.4     374 2237.59   400.5 2235.22   423.6  2235.3
   441.3 2241.01   470.8 2258.48   500.7 2282.33   509.8  2285.6   532.6 2305.15
   578.1 2336.61   635.9 2372.19   655.6 2386.29   664.7    2390     730 2434.32
#Mann= 3, -1 ,  0
       0     0.1       0   296.8   0.045       0   323.8     0.1       0
Bank Sta=296.8,323.8
XS Rating Curve= 0 ,0
Exp/Cntr(USF)=0,0
Exp/Cntr=0.3,0.1

Type RM Length L Ch R = 1 ,9925    ,233.8,242,244.5
XS GIS Cut Line= 2
2332616.54242152718689.582695013 2333107.9310617719206.439150261
#Sta/Elev= 30
       0 2329.54    36.2 2310.49    57.5 2301.63    81.5 2295.92    92.4  2295.5
   120.9 2290.68   148.5 2284.07   179.4 2268.88   208.5 2249.98   231.3 2238.25
   254.9 2223.06   272.3 2215.06   286.4 2214.46   295.5 2214.96     322 2217.53
   333.3 2216.78   358.8 2218.02   387.1 2229.49   396.8 2235.18   406.9 2245.96
     441 2263.27   468.6  2281.8   539.9 2325.08   590.8 2358.38   643.9 2394.28
   650.2 2399.89   658.7 2409.58   667.3 2416.57   694.9  2435.6   713.2  2443.1
#Mann= 3, -1 ,  0
       0     0.1       0   272.3   0.045       0   295.5     0.1       0
Bank Sta=272.3,295.5
XS Rating Curve= 0 ,0
Exp/Cntr(USF)=0,0
Exp/Cntr=0.3,0.1

Type RM Length L Ch R = 1 ,9683    ,302.7,305.5,305.9
XS GIS Cut Line= 2
2332555.24087165718720.2065111152332757.25186717719399.707583705
#Sta/Elev= 30
       0  2338.8    38.6 2319.14    51.1 2311.26    63.6 2305.69    76.1 2297.48
   117.3 2277.09   147.1 2266.67   238.9 2246.78   258.9 2238.54   284.6 2221.87
   301.5 2214.01   313.6 2212.53   322.3 2209.61   347.4 2208.65   358.6  2206.1
   371.5 2205.39   381.1 2206.21   390.8 2208.77   409.8 2219.53     435 2227.84
   451.7 2237.77   476.7 2248.98   497.6 2260.49   510.1 2269.34   518.5 2272.93
   534.5 2282.08   564.5 2294.75   618.6 2321.41     627 2324.56   708.9 2366.52
#Mann= 3, -1 ,  0
       0     0.1       0   358.6   0.045       0   381.1     0.1       0
Bank Sta=358.6,381.1
XS Rating Curve= 0 ,0
Exp/Cntr(USF)=0,0
Exp/Cntr=0.3,0.1

Type RM Length L Ch R = 1 ,9377    ,442.3,437.7,438.8
XS GIS Cut Line= 3
2332320.30285686718798.259386729 2332384.6339946719179.218774566
2332488.90900916 719504.54781539
#Sta/Elev= 30
       0 2350.27    39.5 2323.33    55.7 2314.06    84.1 2295.18   124.7 2267.11
     149  2248.7   173.3 2226.41   189.2 2214.45   201.7  2207.5   226.1 2201.15
   236.5 2196.46   250.4 2196.19   258.5 2196.46   274.8 2196.71   282.9 2199.48
   299.1 2198.54   347.8 2199.77     364 2207.22   376.2 2206.52   384.3 2208.46
     398 2216.19   438.8    2245   459.8 2255.16   476.6 2267.14   514.4 2291.49
   555.2 2315.35   587.9 2337.02   622.9 2353.55   682.4 2383.78     728 2408.73
#Mann= 3, -1 ,  0
       0     0.1       0   236.5   0.045       0   258.5     0.1       0
#XS Ineff= 2 , 0
                          293.43         2223.45
Permanent Ineff=
       F       F
Bank Sta=236.5,258.5
XS Rating Curve= 0 ,0
Exp/Cntr(USF)=0,0
Exp/Cntr=0.3,0.1

Type RM Length L Ch R = 1 ,8939    ,257.3,255.9,256.7
XS GIS Cut Line= 2
2331863.62513192719015.975908209 2332205.3552833719631.016683942
#Sta/Elev= 30
       0    2320    33.4 2309.98    56.3 2300.39     119 2268.31   147.8 2251.94
   163.1 2246.33   182.3 2236.57   193.6 2227.34   202.7 2222.53   224.8 2207.89
   248.5 2201.31   269.4 2188.63   275.9 2187.31   295.4 2187.64   336.6 2185.54
  355.442180.749   376.6 2179.97   390.3 2180.65   430.8 2197.22   440.7 2203.49
   454.4 2217.98   478.8 2236.12   542.5  2272.9   557.2 2282.45   569.4 2287.64
   604.3 2308.56   655.7 2340.69   669.5 2348.25   678.6 2356.23   703.6    2372
#Mann= 3, -1 ,  0
       0     0.1       0  355.44   0.045       0   390.3     0.1       0
Bank Sta=355.44,390.3
XS Rating Curve= 0 ,0
Exp/Cntr(USF)=0,0
Exp/Cntr=0.3,0.1

Type RM Length L Ch R = 1 ,8684    ,227.2,227.6,228.6
XS GIS Cut Line= 2
2331619.32288275 719189.40651258  2332041.987076719740.759694738
#Sta/Elev= 30
       0 2347.83    47.4 2314.83    60.2 2307.31    74.6 2300.74      86 2292.81
   115.6 2275.15   206.4 2226.94   260.1 2204.27   282.9  2189.5     292 2181.38
   297.1 2178.06   302.1 2172.66   305.7 2171.11   312.2 2170.68   325.7 2171.22
   342.8 2174.46   352.5 2177.75   362.6 2178.83   372.7 2183.84   385.6 2177.77
   394.2 2177.25     408 2183.93   415.6 2182.91   422.2 2183.89     437  2190.5
   496.9 2227.54   516.8 2242.93   555.6 2268.76   665.2 2333.19   694.7 2353.08
#Mann= 3, -1 ,  0
       0     0.1       0   305.7   0.045       0   325.7     0.1       0
Bank Sta=305.7,325.7
XS Rating Curve= 0 ,0
Exp/Cntr(USF)=0,0
Exp/Cntr=0.3,0.1

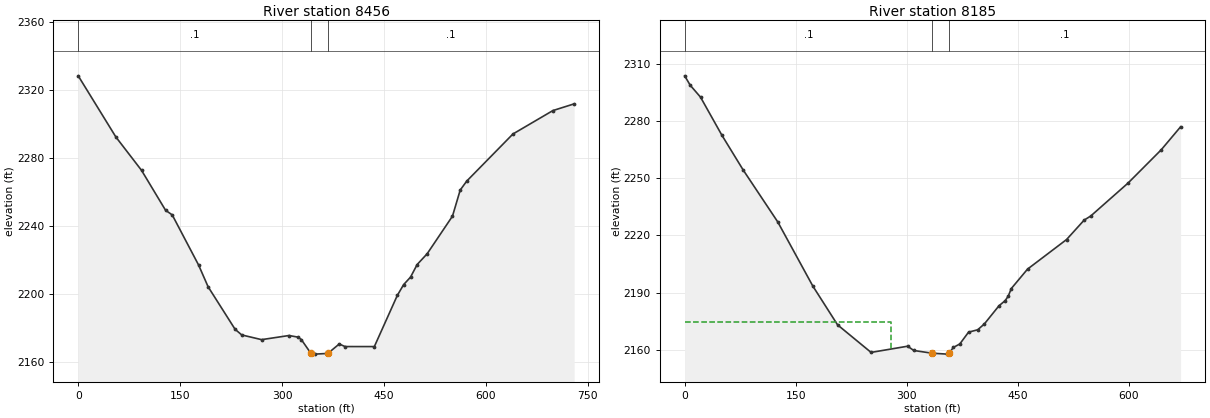
Type RM Length L Ch R = 1 ,8456    ,268.1,271.4,276.7
XS GIS Cut Line= 2
2331434.97566879719295.6016088162331851.87947795719894.843808523
#Sta/Elev= 30
       0 2328.15    55.5 2292.14    93.2 2272.56   128.6 2249.06   138.4 2246.34
   177.2 2216.85   191.2 2204.07   230.9 2179.07   240.7 2175.74   269.9 2172.97
   310.3  2175.4   323.5 2174.45   328.4 2173.02   342.62164.862   347.9 2164.45
   367.4 2164.85   384.2  2170.4   392.8  2168.9   435.9 2168.89   469.7 2198.98
     479 2205.33   489.2 2209.77   498.9 2217.15   513.6 2223.47   550.9 2245.61
   562.3 2260.98     572 2266.28   639.9 2293.94   698.7 2307.71     730 2311.66
#Mann= 3, -1 ,  0
       0     0.1       0   342.6   0.045       0   367.4     0.1       0
Bank Sta=342.6,367.4
XS Rating Curve= 0 ,0
Exp/Cntr(USF)=0,0
Exp/Cntr=0.3,0.1

Type RM Length L Ch R = 1 ,8185    ,364.5,354.5,340.1
XS GIS Cut Line= 3
 2331315.8810282719376.3701251852331421.19215159719809.917751861
2331524.27837994720008.787940162
#Sta/Elev= 30
       0 2303.77     7.5 2298.82    21.4 2292.58    50.2 2272.64      79 2254.37
   125.8 2227.06   173.1 2193.44   206.6 2173.03   251.9 2158.56   301.3 2161.82
   309.6 2159.57   334.3 2158.15   354.8 2157.66   357.1 2158.02   363.1 2161.18
   371.8 2162.99   383.6 2169.19     396 2170.44     405 2173.52   424.8 2183.07
     433  2185.7   437.2 2188.05   441.4  2192.1   463.3 2202.28   516.1 2217.83
   539.9 2228.05   548.7 2230.16   599.2 2247.48   643.9  2264.9   670.2 2277.02
#Mann= 3, -1 ,  0
       0     0.1       0   334.3   0.045       0   357.1     0.1       0
#XS Ineff= 2 , 0
          279.49 2174.45
Permanent Ineff=
       F       F
Bank Sta=334.3,357.1
XS Rating Curve= 0 ,0
Exp/Cntr(USF)=0,0
Exp/Cntr=0.3,0.1