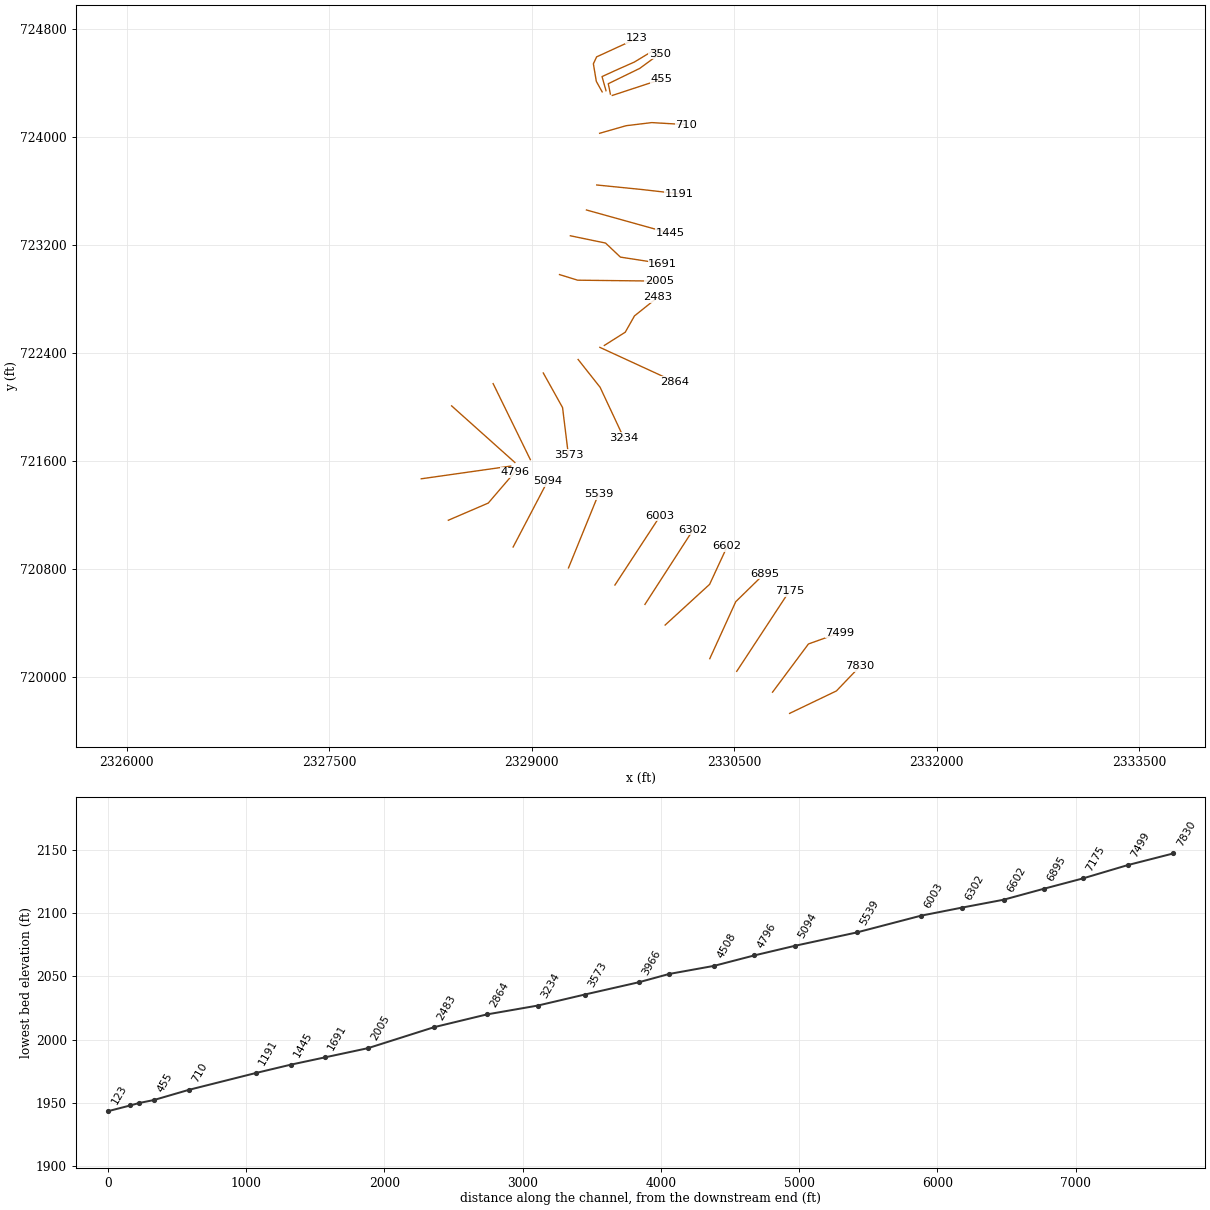
HEC-RAS study LTBLACKFK.prj: LTBLACKFK

--- LTBLACKFK.g01 (geometry) --- (continued)

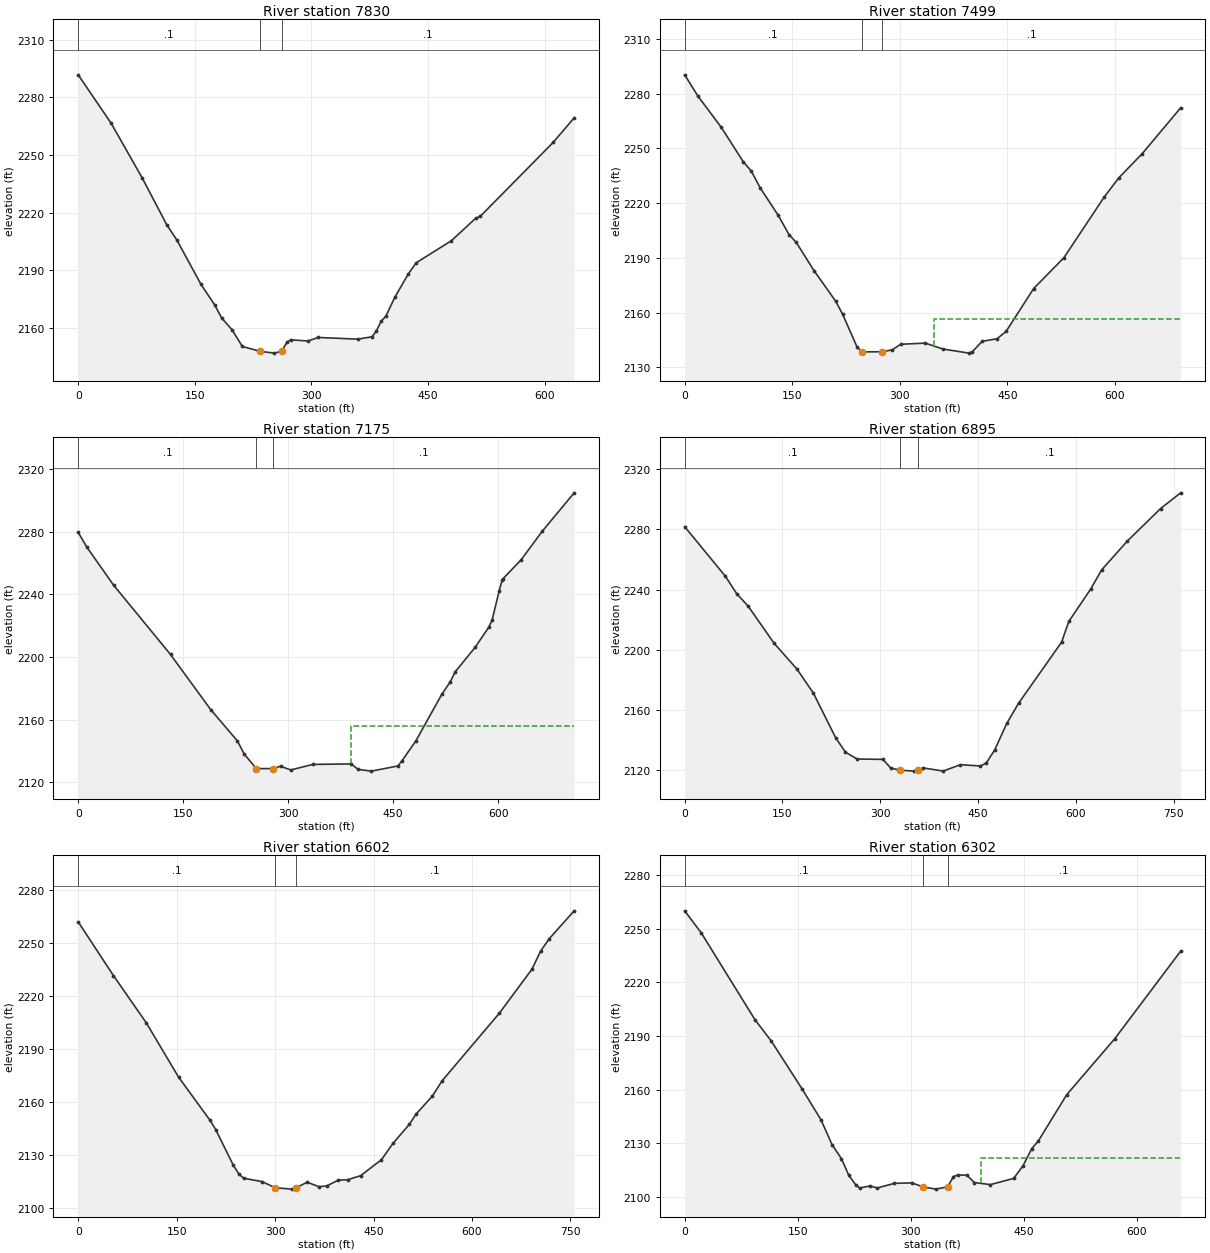
Type RM Length L Ch R = 1 ,7830    ,325.3,330.8,338.7
XS GIS Cut Line= 3
2330909.87476872719731.458210262 2331256.3331863719897.640871005
2331431.77942459720080.649447151
#Sta/Elev= 30
       0 2291.78    42.5 2266.49    82.4 2238.04   113.9 2213.73   126.8 2205.88
   157.8 2182.81   175.6    2172   184.4  2165.3   197.8 2159.14   211.1 2150.42
   233.9 2147.93   251.9 2146.97   261.72147.928   268.7 2152.75   273.2  2153.9
   295.4 2153.28   308.8 2155.12   359.8 2154.24   377.8 2155.48   383.2 2158.32
   389.8 2163.66   395.6 2166.15   407.1 2175.95   424.5 2188.19   434.7 2193.99
     480 2205.47   511.1 2217.12     517 2218.12   610.8  2256.6   637.8  2269.4
#Mann= 3, -1 ,  0
       0     0.1       0   233.9   0.045       0   261.7     0.1       0
Bank Sta=233.9,261.7
XS Rating Curve= 0 ,0
Exp/Cntr(USF)=0,0
Exp/Cntr=0.3,0.1

Type RM Length L Ch R = 1 ,7499    ,323.1,323.8,324.9
XS GIS Cut Line= 3
2330783.23079073719888.4589330212331049.12512901720245.508412439
2331281.23108412720328.508527157
#Sta/Elev= 30
       0 2290.41    18.3 2278.83    50.8 2261.76    81.9 2242.63    92.7 2237.74
   105.6 2228.24   130.6 2213.27   145.5 2202.76   155.6 2198.49   180.4 2182.99
   210.4 2166.36   220.3  2159.1   240.3  2141.2     247 2138.45   275.2 2138.49
   289.6 2139.56   301.3 2142.61   335.6 2143.25     360 2140.01   396.7 2137.75
   401.4 2138.58   414.8 2144.22   435.7 2145.64   448.4 2149.71   486.7 2173.17
   529.1 2190.18     585 2223.31   605.6 2233.95   638.2 2247.21   691.7 2272.28
#Mann= 3, -1 ,  0
       0     0.1       0     247   0.045       0   275.2     0.1       0
#XS Ineff= 2 , 0
                          348.23         2156.31
Permanent Ineff=
       F       F
Bank Sta=247,275.2
XS Rating Curve= 0 ,0
Exp/Cntr(USF)=0,0
Exp/Cntr=0.3,0.1

Type RM Length L Ch R = 1 ,7175    ,277.6,280.7,282.4
XS GIS Cut Line= 2
2330518.10706702720042.8943158832330907.01584798720635.344786488
#Sta/Elev= 30
       0 2279.53    12.3 2270.15    50.6 2245.85   131.9 2201.64   189.3 2166.51
   227.6 2146.46     237 2138.28   254.5 2128.85   278.82128.869   289.1 2130.39
   303.6    2128   335.3 2131.53   390.2 2131.85   399.9 2128.36     419 2127.25
   456.7 2130.54   462.1 2133.44   482.7 2146.68   519.5 2176.18   531.8 2184.31
   538.6  2190.5   567.3 2206.27   586.5 2218.89   591.3 2223.39   601.5 2242.09
   605.6  2248.9   606.9 2249.91   632.9 2262.03     663 2280.18   708.7 2304.76
#Mann= 3, -1 ,  0
       0     0.1       0   254.5   0.045       0   278.8     0.1       0
#XS Ineff= 2 , 0
                          389.89         2156.03
Permanent Ineff=
       F       F
Bank Sta=254.5,278.8
XS Rating Curve= 0 ,0
Exp/Cntr(USF)=0,0
Exp/Cntr=0.3,0.1

Type RM Length L Ch R = 1 ,6895    ,298,293.1,285.5
XS GIS Cut Line= 3
 2330318.2922714720136.4684481392330510.68667357 720558.58919973
2330722.80255514720765.958163774
#Sta/Elev= 30
       0 2281.89    62.4 2248.87    79.9 2237.19    97.5  2228.9   137.1 2204.27
   172.2 2187.06   197.4 2171.05   231.4 2141.49   246.5 2131.75   264.5  2127.2
   304.1 2126.96     316 2121.15   330.5 2119.78   351.7 2119.14   358.3 2119.81
   365.6 2121.27   396.4  2119.2   422.8  2123.4   453.6 2122.58   462.3 2124.43
   475.3 2133.14   493.9 2150.88     512 2164.33   577.9 2204.93     589 2218.76
   622.4 2240.22   639.3 2253.06   678.5 2272.16   729.8 2293.94   760.5 2304.41
#Mann= 3, -1 ,  0
       0     0.1       0   330.5   0.045       0   358.3     0.1       0
Bank Sta=330.5,358.3
XS Rating Curve= 0 ,0
Exp/Cntr(USF)=0,0
Exp/Cntr=0.3,0.1

Type RM Length L Ch R = 1 ,6602    ,293.8,300,302.2
XS GIS Cut Line= 3
2329987.72791315720385.6872896472330317.09082443720687.148943303
2330447.16540937720967.597407231
#Sta/Elev= 30
       0 2261.98    53.7 2231.49   103.6 2204.79   152.8    2174     201 2149.38
   209.5 2144.18   236.2 2124.08   244.6 2119.11   251.9 2116.63   280.2 2114.68
   300.1 2111.23   325.1 2110.43   332.22111.211   348.8 2114.36   366.6 2111.81
   378.4 2112.22   396.3 2115.51   410.5 2115.74   430.3 2118.07     462 2127.11
   479.6 2136.37   504.6 2147.21   514.9 2153.06   539.4 2163.11   554.6 2171.93
   641.7 2210.21   691.3 2235.14   704.5 2245.39   717.7 2252.43   755.6 2268.23
#Mann= 3, -1 ,  0
       0     0.1       0   300.1   0.045       0   332.2     0.1       0
Bank Sta=300.1,332.2
XS Rating Curve= 0 ,0
Exp/Cntr(USF)=0,0
Exp/Cntr=0.3,0.1

Type RM Length L Ch R = 1 ,6302    ,291,298.4,291.4
XS GIS Cut Line= 2
2329838.06037608720538.515530465 2330195.1231224721091.109367606
#Sta/Elev= 30
       0 2260.11    22.2 2247.63    93.1 2199.23   114.5 2187.42   155.6 2160.47
   180.8  2143.1   195.5 2129.12     208 2121.29   217.5 2112.13     227 2106.59
     232  2104.9   246.1    2106   255.6 2104.89   278.3 2107.49   301.4 2107.75
   315.9 2105.51   333.3 2104.24   348.92105.518   356.4 2111.19   362.2 2112.21
   374.6 2111.98   384.2 2107.94   405.6 2106.77   436.5 2110.26     449 2117.47
   460.4 2126.92   469.2 2131.25   506.8 2157.13   570.5 2188.47   657.9 2237.49
#Mann= 3, -1 ,  0
       0     0.1       0   315.9   0.045       0   348.9     0.1       0
#XS Ineff= 2 , 0
                          393.72         2121.72
Permanent Ineff=
       F       F
Bank Sta=315.9,348.9
XS Rating Curve= 0 ,0
Exp/Cntr(USF)=0,0
Exp/Cntr=0.3,0.1

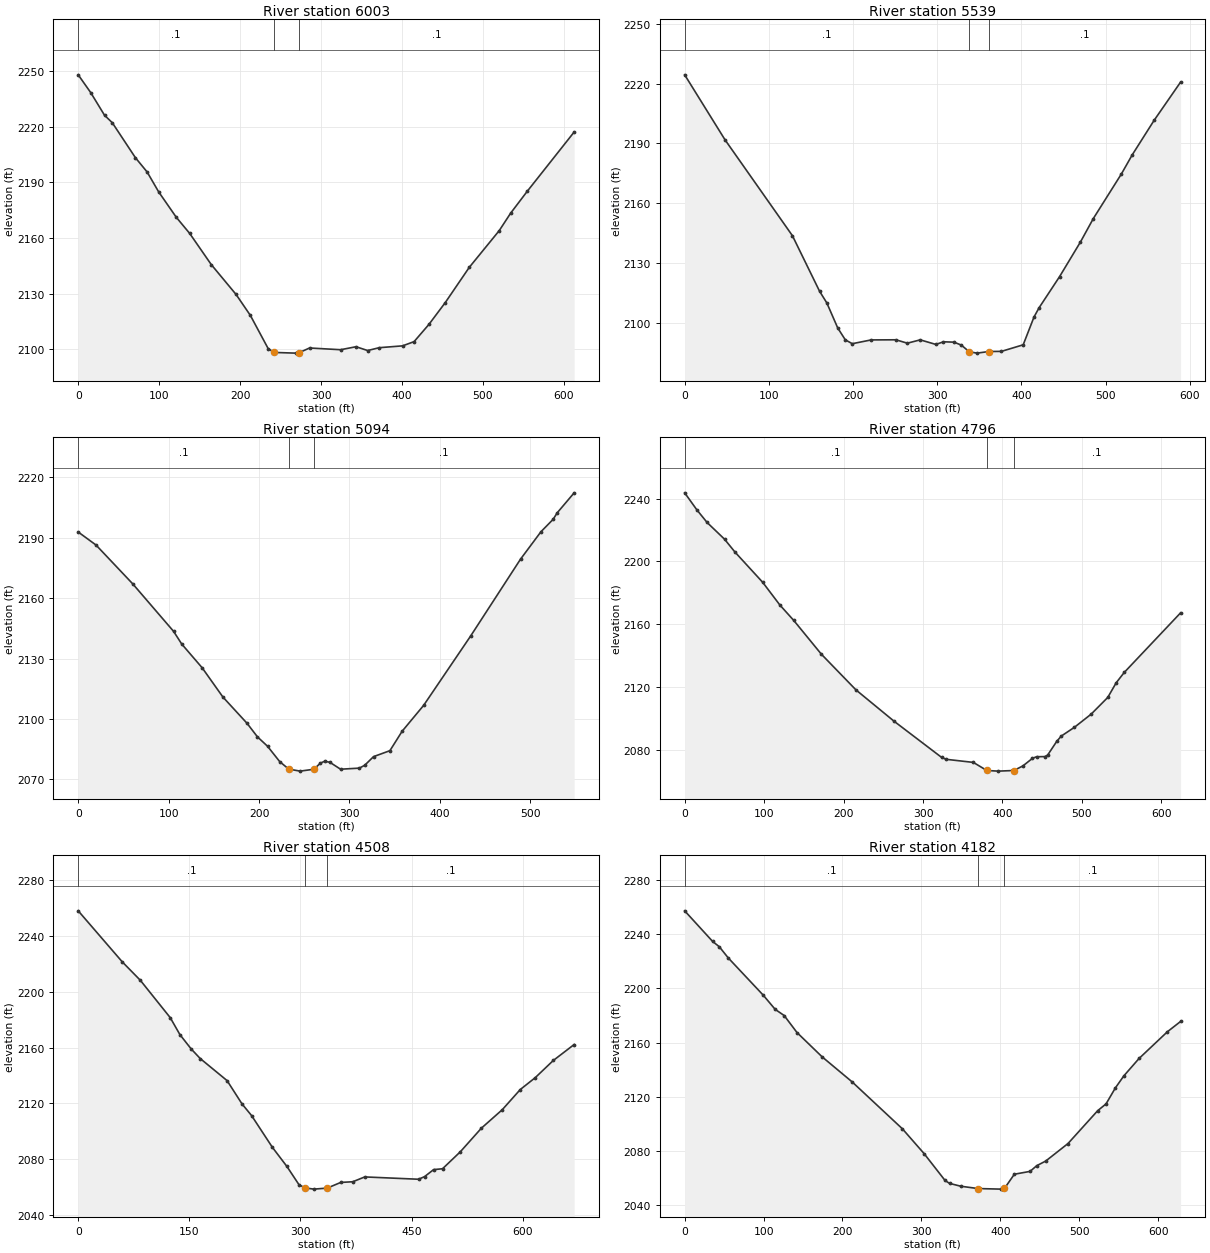
Type RM Length L Ch R = 1 ,6003    ,459.3,464.2,464.1
XS GIS Cut Line= 2
2329615.76937959720681.9731423792329951.11503277721194.606358082
#Sta/Elev= 30
       0 2248.06    15.4  2238.5    32.5 2226.24    42.1  2222.2    70.7  2203.3
    85.1 2195.63    99.4 2184.86   121.1 2171.18   137.7 2162.44   164.4 2145.59
     195 2129.49   212.6 2118.22   234.6  2100.3   241.9 2098.19   268.5 2097.82
   273.22098.117   285.7 2100.59   324.1 2099.66   343.2 2101.27   357.5 2099.22
   371.9 2100.76   400.6 2101.74   414.9 2104.03   433.2 2113.32   453.4 2125.11
     483  2144.1   520.1 2163.98   534.1 2173.35   554.5  2185.1   612.6 2217.19
#Mann= 3, -1 ,  0
       0     0.1       0   241.9   0.045       0   273.2     0.1       0
Bank Sta=241.9,273.2
XS Rating Curve= 0 ,0
Exp/Cntr(USF)=0,0
Exp/Cntr=0.3,0.1

Type RM Length L Ch R = 1 ,5539    ,446.1,445,442.4
XS GIS Cut Line= 2
2329271.92661519720808.7770565832329494.03490844721354.396548017
#Sta/Elev= 30
       0 2224.49    47.9 2191.84     128 2143.62   160.2 2115.74   168.9  2109.8
   181.8 2097.26   190.8 2091.29   199.1 2089.35   221.5 2091.25   250.9 2091.31
   264.5 2089.61   279.8 2091.28   298.4 2088.98   307.4 2090.31     320 2090.12
   328.7 2088.62   338.1 2085.27   347.3 2084.61   361.4 2085.42   376.2 2085.49
   402.1 2088.79     415 2102.81     421 2107.43   445.3 2123.05   470.1 2140.46
   485.4 2152.25   518.7 2174.63   531.6 2184.25   557.5 2201.54   589.1 2220.85
#Mann= 3, -1 ,  0
       0     0.1       0   338.1   0.045       0   361.4     0.1       0
Bank Sta=338.1,361.4
XS Rating Curve= 0 ,0
Exp/Cntr(USF)=0,0
Exp/Cntr=0.3,0.1

Type RM Length L Ch R = 1 ,5094    ,302.3,297.9,295.3
XS GIS Cut Line= 2
2328861.92083501720963.7116173412329116.38683538721449.733202814
#Sta/Elev= 30
       0 2192.75    19.7 2186.29    60.4 2166.99   105.5 2143.47   114.5 2137.18
   137.1  2125.4   160.1 2110.86   186.8 2097.84   198.3 2091.11   209.4 2086.49
   222.9 2078.85  232.912075.127   245.5 2074.13   260.6 2075.06     268 2078.12
   272.6 2079.03   278.4 2078.51   290.2 2075.08     311 2075.62   316.9 2077.03
   326.7 2081.32   344.8 2084.28   358.3  2093.9   382.1 2106.75   434.1 2141.16
   489.3  2179.3   511.9  2192.9   525.4 2199.07   529.9  2202.3   548.6 2212.19
#Mann= 3, -1 ,  0
       0     0.1       0  232.91   0.045       0   260.6     0.1       0
Bank Sta=232.91,260.6
XS Rating Curve= 0 ,0
Exp/Cntr(USF)=0,0
Exp/Cntr=0.3,0.1

Type RM Length L Ch R = 1 ,4796    ,298.6,288.8,277.9
XS GIS Cut Line= 3
2328382.07812322721162.0587633092328677.57597698 721289.11103674
2328874.52819643 721518.73466663
#Sta/Elev= 30
       0  2243.7    15.3 2232.88    28.2 2224.82    50.2 2214.15    63.2 2206.03
    98.1 2186.76   119.8 2172.25   137.3 2162.41   172.1 2140.88   215.6 2118.17
   263.5 2098.24   323.5 2075.14   329.2 2073.96   363.3    2072   380.3 2066.85
   394.5 2066.44   414.3 2066.83   425.7 2069.76   437.7 2074.58   442.9 2075.61
   453.5  2075.7   456.9 2076.71   468.2 2085.33   473.9 2088.73   490.4  2094.3
   511.5 2102.69   532.5 2113.38   543.1 2122.71   553.3 2129.33   624.2 2167.28
#Mann= 3, -1 ,  0
       0     0.1       0   380.3   0.045       0   414.3     0.1       0
Bank Sta=380.3,414.3
XS Rating Curve= 0 ,0
Exp/Cntr(USF)=0,0
Exp/Cntr=0.3,0.1

Type RM Length L Ch R = 1 ,4508    ,338,325.3,311.6
XS GIS Cut Line= 2
2328181.15158115721468.9391537232328844.07808284721563.036636314
#Sta/Elev= 30
       0 2258.19    59.5 2221.51    83.9 2208.27   124.3 2181.41   137.3 2169.26
   152.5 2158.98   164.7 2152.09     201 2136.22   221.2 2119.45     234 2111.15
   262.2 2088.26   281.8 2074.54     298  2061.5   306.1 2059.15   318.2 2058.26
   336.22059.003   354.5 2063.08   370.7 2063.56   386.9 2067.03   459.6 2065.36
   467.7 2067.26   479.8 2072.27   491.9  2072.9   515.9 2085.08   544.4 2102.07
   572.5 2115.29   596.9 2129.83   617.1 2138.35   641.4 2150.67   669.6 2162.15
#Mann= 3, -1 ,  0
       0     0.1       0   306.1   0.045       0   336.2     0.1       0
Bank Sta=306.1,336.2
XS Rating Curve= 0 ,0
Exp/Cntr(USF)=0,0
Exp/Cntr=0.3,0.1

Type RM Length L Ch R = 1 ,4182    ,220.7,216.5,213.9
XS GIS Cut Line= 2
2328406.11623732722009.123488016 2328874.4926624721590.052582849
#Sta/Elev= 30
       0 2257.32    35.4 2234.74    43.9 2230.79    55.2 2222.56    99.4 2195.15
   114.7 2184.57   126.1 2180.02   142.3 2167.49   174.2 2149.51   212.1 2131.09
   275.9  2096.4   303.3 2078.16     330 2058.23   335.7 2056.09   349.9    2054
   371.8 2052.28   400.8 2051.86   405.3 2052.41   417.8 2062.86   437.7 2064.96
   446.2 2069.18   457.5 2072.57   485.8 2085.53   523.4 2109.77     534 2114.79
   545.8 2126.57   556.6 2135.51   575.8  2148.3   611.8 2168.07   628.5 2175.66
#Mann= 3, -1 ,  0
       0     0.1       0   371.8   0.045       0   405.3     0.1       0
Bank Sta=371.8,405.3
XS Rating Curve= 0 ,0
Exp/Cntr(USF)=0,0
Exp/Cntr=0.3,0.1

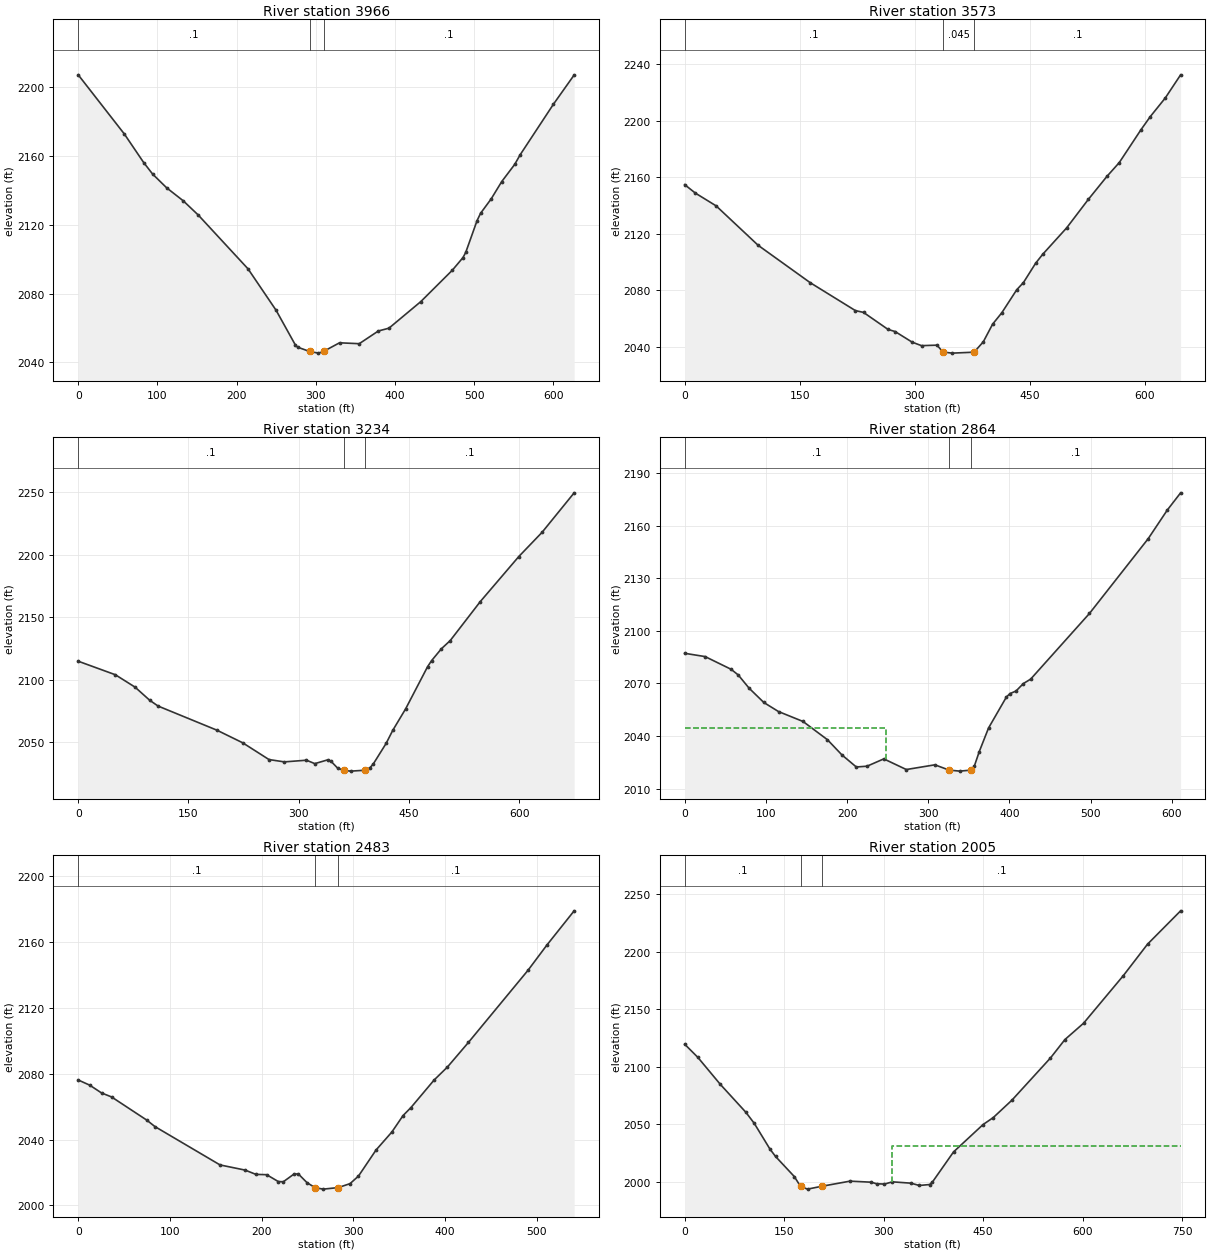
Type RM Length L Ch R = 1 ,3966    ,395.9,392.4,391.3
XS GIS Cut Line= 2
2328713.92915054722173.628130468 2328989.1604765721611.039800534
#Sta/Elev= 30
       0 2207.02    58.4 2172.57    82.7 2156.06      94 2149.37   111.8 2141.35
   132.5 2133.91   151.5 2125.64   214.5 2094.31   249.9 2070.27   274.1 2050.23
   277.1 2048.83   292.1 2046.38   303.3 2045.39  309.832046.402     330 2051.39
   354.9 2050.87     379 2058.24   392.4 2059.88   432.6  2075.3   472.5 2093.56
   485.9 2100.88   489.4 2103.91   503.7 2122.35   508.1 2126.59   521.5 2134.96
   534.9 2145.06   551.2 2154.98   558.2 2160.65     600 2189.86   626.3 2206.94
#Mann= 3, -1 ,  0
       0     0.1       0   292.1   0.045       0  309.83     0.1       0
Bank Sta=292.1,309.83
XS Rating Curve= 0 ,0
Exp/Cntr(USF)=0,0
Exp/Cntr=0.3,0.1

Type RM Length L Ch R = 1 ,3573    ,333.7,338.9,345.4
XS GIS Cut Line= 3
2329084.98858275722252.9561694082329227.88567071721996.675668711
2329271.02405281721645.765454645
#Sta/Elev= 30
       0 2154.88    13.9 2148.91      41 2139.87    95.9 2111.93   163.9 2085.46
   222.7 2065.76   233.3 2064.48   265.4  2052.4   274.5 2050.94   296.9 2043.38
     309 2040.95   329.2  2041.3  337.062036.378   349.3 2035.66   377.6 2036.33
   389.6 2043.69   401.7 2056.13   413.8 2064.28   433.2  2080.5     442 2085.63
   457.9 2099.31   467.1  2105.6   498.5  2124.4   526.5 2144.37   550.8 2160.67
     567 2170.51   595.2 2193.67   607.3 2202.94     627 2216.21     647 2232.58
#Mann= 3, -1 ,  0
       0     0.1       0  337.06   0.045       0   377.6     0.1       0
Bank Sta=337.06,377.6
XS Rating Curve= 0 ,0
Exp/Cntr(USF)=0,0
Exp/Cntr=0.3,0.1

Type RM Length L Ch R = 1 ,3234    ,359.3,370.8,379.1
XS GIS Cut Line= 3
2329343.22035223722352.7653804072329506.25309418722146.422190006
2329680.67468858721773.538406932
#Sta/Elev= 30
       0  2114.8    50.5 2103.99    77.3  2094.1    97.2 2083.62   108.6 2078.98
   188.7 2059.69   223.8  2049.6   259.5 2036.22   280.4 2034.37   310.5  2035.7
   321.8 2032.98   339.4 2035.99   343.6 2035.03   352.8 2029.42   361.1 2027.55
   370.7 2026.98   390.2 2027.69   396.8 2029.69   401.2 2032.55   418.8 2049.09
   427.8  2059.5   445.4 2076.77   475.2 2110.39   480.7 2115.27     494 2124.73
     506 2131.27     547 2162.49   599.3 2198.42   630.9 2217.73   674.6 2249.33
#Mann= 3, -1 ,  0
       0     0.1       0   361.1   0.045       0   390.2     0.1       0
Bank Sta=361.1,390.2
XS Rating Curve= 0 ,0
Exp/Cntr(USF)=0,0
Exp/Cntr=0.3,0.1

Type RM Length L Ch R = 1 ,2864    ,359.2,380.4,397.9
XS GIS Cut Line= 2
2329504.17760294722442.5633614892330059.17025536722187.155067706
#Sta/Elev= 30
       0  2087.2    25.2 2085.32    57.2 2078.07      66 2074.82    79.4 2067.26
    97.5 2059.12   115.6 2053.94   145.8 2048.28   175.9 2037.86   193.7 2029.19
   211.4 2022.31   224.6 2022.75   245.3 2026.93     273 2020.85   308.2 2023.54
   325.8 2020.51     339 2019.94   352.92020.535   356.7 2022.68   362.9 2031.12
   374.3 2044.56   396.3 2062.24   400.7  2064.2   408.1 2065.65   417.2 2069.93
   426.2 2072.47   498.6 2109.94     571 2152.65   594.4 2168.91   610.9  2178.8
#Mann= 3, -1 ,  0
       0     0.1       0   325.8   0.045       0   352.9     0.1       0
#XS Ineff= 2 , 0
          247.65 2044.69
Permanent Ineff=
       F       F
Bank Sta=325.8,352.9
XS Rating Curve= 0 ,0
Exp/Cntr(USF)=0,0
Exp/Cntr=0.3,0.1

Type RM Length L Ch R = 1 ,2483    ,500,477.6,467
XS GIS Cut Line= 4
2329537.50528085722456.7866668322329692.30446516722554.755339953
 2329760.5942519722675.5146449522329931.38055167722812.005990901
#Sta/Elev= 30
       0 2076.14    12.6 2072.98    25.4 2068.28    36.3 2065.87    74.7  2051.8
    83.6 2047.88   154.6 2024.59     182 2021.45   193.7 2018.86   205.4 2018.67
   218.1  2014.5   223.6 2014.39   234.8 2018.89   239.8 2019.21   249.5 2013.78
   258.3 2010.79   267.1 2009.91  283.452010.844   296.3 2013.24   305.5 2017.83
   324.6 2033.61   341.9 2044.57   354.1 2054.55   362.7 2059.41     388 2076.15
   402.5 2084.02   425.3  2098.9   490.4 2142.78   510.8 2157.96   540.6 2178.79
#Mann= 3, -1 ,  0
       0     0.1       0   258.3   0.045       0  283.45     0.1       0
Bank Sta=258.3,283.45
XS Rating Curve= 0 ,0
Exp/Cntr(USF)=0,0
Exp/Cntr=0.3,0.1

Type RM Length L Ch R = 1 ,2005    ,331.3,314.8,308
XS GIS Cut Line= 3
2329205.28186629722981.5225263512329339.93975133722939.987410328
2329946.58438345722933.146220729
#Sta/Elev= 30
       0 2119.49    19.8 2108.05    53.8 2084.48    92.2 2060.27     105 2050.51
   128.6 2028.17     137 2021.78   165.2 2004.35   174.7 1995.72   185.2 1993.37
   207.1  1995.9   249.2 2000.31   281.2 1999.41   289.2 1998.05   301.2 1997.77
   313.2 1999.72   341.2 1998.54   353.6 1996.56   369.2 1997.36   373.4 1999.49
   405.3 2025.75   449.8 2049.56   465.2 2055.65   493.2 2070.71   551.4 2107.49
   573.2 2123.53   601.2 2137.68   661.2 2179.12   697.7 2206.51   747.6 2235.54
#Mann= 3, -1 ,  0
       0     0.1       0   174.7   0.045       0   207.1     0.1       0
#XS Ineff= 2 , 0
                          312.49         2030.69
Permanent Ineff=
       F       F
Bank Sta=174.7,207.1
XS Rating Curve= 0 ,0
Exp/Cntr(USF)=0,0
Exp/Cntr=0.3,0.1

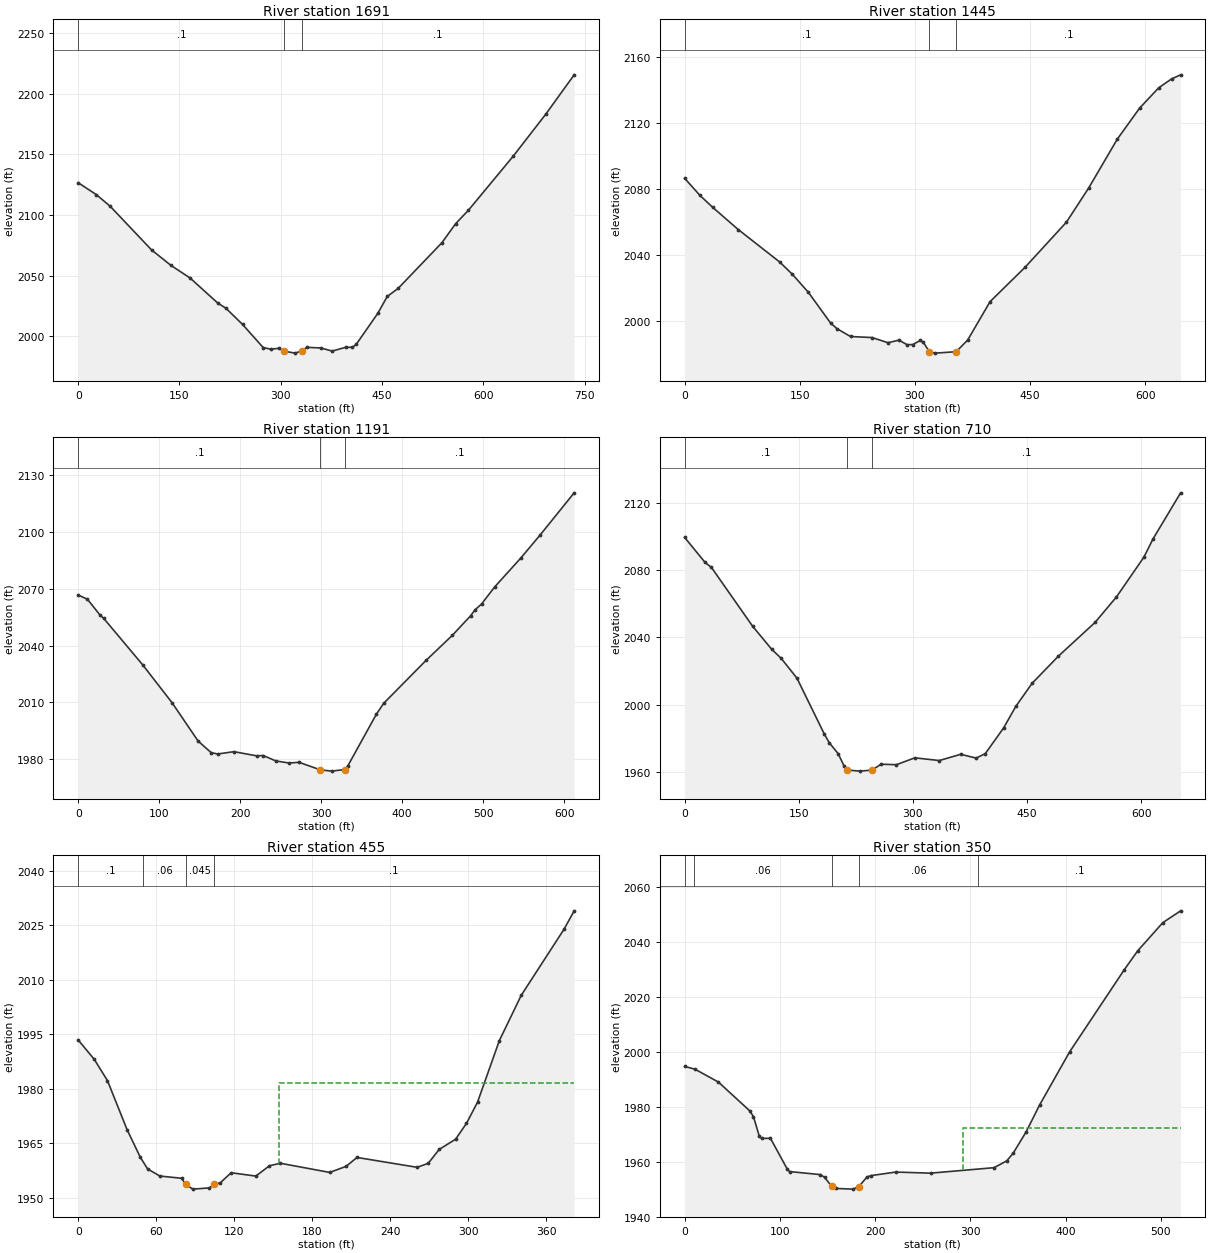
Type RM Length L Ch R = 1 ,1691    ,236.5,246,252.1
XS GIS Cut Line= 4
2329285.82839689723268.903310932 2329546.5860944723214.986652358
2329656.47366112723110.9419564912329969.78461868723062.599617616
#Sta/Elev= 30
       0 2126.66    26.9 2116.83    47.3 2107.26   108.6 2071.23   137.1 2058.55
   165.8 2047.98   206.6  2027.4   218.9 2023.02   243.4 2009.74     274 1990.59
   285.7 1989.26     297 1990.02   305.5 1987.59   321.3 1986.02   330.9 1987.85
   338.7  1990.8   359.2 1990.28   376.2 1987.72     396  1990.8   406.2 1990.87
   411.7 1993.19   443.9 2018.98   457.8 2032.81     474 2039.51   538.7 2077.14
   559.1 2092.89   577.9  2103.9     644 2148.36   692.4 2183.13   734.6 2215.73
#Mann= 3, -1 ,  0
       0     0.1       0   305.5   0.045       0   330.9     0.1       0
Bank Sta=305.5,330.9
XS Rating Curve= 0 ,0
Exp/Cntr(USF)=0,0
Exp/Cntr=0.3,0.1

Type RM Length L Ch R = 1 ,1445    ,251,253.4,256.2
XS GIS Cut Line= 2
2329404.89307545723460.0510532042330027.56844822723286.731752385
#Sta/Elev= 30
       0 2086.24      20 2075.84    36.6 2068.61    69.8  2055.2   123.8 2035.52
   140.4 2028.05   161.2 2017.14   190.2 1998.49   198.6 1995.06   216.1 1990.36
   244.2 1989.72     265 1986.59   279.2 1988.16   289.9 1985.38   297.3  1985.5
   307.1 1987.98   310.7 1987.03     319 1981.06   326.5 1980.28   353.8 1981.14
   368.8 1988.22     398  2011.5   443.5 2032.28   497.5 2059.67   526.6 2080.47
   563.9 2110.09     593 2128.87   617.9 2141.18   634.5  2146.5   646.3 2148.98
#Mann= 3, -1 ,  0
       0     0.1       0     319   0.045       0   353.8     0.1       0
Bank Sta=319,353.8
XS Rating Curve= 0 ,0
Exp/Cntr(USF)=0,0
Exp/Cntr=0.3,0.1

Type RM Length L Ch R = 1 ,1191    ,478.4,481.3,484.9
XS GIS Cut Line= 3
2329480.93202794723645.2442352322329816.57163212723611.552382384
 2330089.6958249723580.080926424
#Sta/Elev= 30
       0 2066.75    11.3 2064.55    27.4 2055.94    31.4 2054.46    79.6 2029.86
   115.8 2009.88     148 1989.59   164.1 1983.47   172.1 1982.73   192.2 1983.96
   220.3 1981.77   228.4 1981.93   244.1 1979.05   260.5 1977.97   272.6 1978.34
   298.9 1974.36   312.8 1973.68   328.9  1974.5   332.9 1976.48     368 2003.67
   377.2 2009.54   429.5 2032.23   461.9 2045.45   484.4 2055.76   489.9 2058.92
     498 2062.03   514.1    2071   546.3 2086.24   570.5 2098.59   612.3 2120.77
#Mann= 3, -1 ,  0
       0     0.1       0   298.9   0.045       0   328.9     0.1       0
Bank Sta=298.9,328.9
XS Rating Curve= 0 ,0
Exp/Cntr(USF)=0,0
Exp/Cntr=0.3,0.1

Type RM Length L Ch R = 1 ,710     ,251.8,254.9,256.5
XS GIS Cut Line= 4
2329502.37538026724028.062661125 2329698.7749855724084.280985497
2329888.72854717724107.3079236662330144.37705907724092.324970994
#Sta/Elev= 30
       0 2099.42    26.8 2084.59    35.2  2081.6    89.2  2046.7   114.2 2033.03
   126.7 2027.61   147.5  2015.8   183.5 1982.53     190 1977.36   201.6 1970.94
   209.7 1963.34   213.8 1961.14   229.9 1960.49   246.1 1961.09   258.1 1964.61
   278.2 1964.31   302.4 1968.39   334.6 1966.79   362.8  1970.5     383 1968.23
   395.1 1970.94   419.1 1986.18   435.1 1998.96   456.6 2012.74   491.2 2028.91
   539.3 2048.93   567.4 2064.08   603.4 2087.69   615.5 2098.63   651.7 2125.98
#Mann= 3, -1 ,  0
       0     0.1       0   213.8   0.045       0   246.1     0.1       0
Bank Sta=213.8,246.1
XS Rating Curve= 0 ,0
Exp/Cntr(USF)=0,0
Exp/Cntr=0.3,0.1

Type RM Length L Ch R = 1 ,455     ,102.8,104.9,106.3
BEGIN DESCRIPTION:
Structure XS 4
END DESCRIPTION:
XS GIS Cut Line= 2
 2329596.4814776724308.4925140472329958.82511099724427.628844869
#Sta/Elev= 30
       0 1993.44    12.3 1988.14    22.5 1982.26    37.6 1968.75    47.8 1961.14
    53.4 1957.94    62.8    1956    79.5 1955.39   82.551953.752    88.1  1952.4
   100.7 1952.73   104.6 1953.68   109.2 1954.13   117.6 1956.91   136.6 1955.99
   147.1 1958.84   155.5 1959.52   193.4    1957     206 1958.66   214.4 1961.12
   260.7  1958.4   269.2 1959.51   277.6 1963.33   290.2 1966.13   298.6 1970.51
   307.1 1976.34   323.9  1993.3   340.7 2005.74   373.6 2023.93   381.4    2029
#Mann= 4, -1 ,  0
       0     0.1       0      50    0.06       0   82.55   0.045       0
   104.6     0.1       0
#XS Ineff= 2 , 0
                          154.15         1981.55
Permanent Ineff=
       F       F
Bank Sta=82.55,104.6
XS Rating Curve= 0 ,0
Exp/Cntr(USF)=0,0
Exp/Cntr=0.3,0.1

Type RM Length L Ch R = 1 ,350     ,67.9,66.3,67.9
BEGIN DESCRIPTION:
Structure XS 3
END DESCRIPTION:
XS GIS Cut Line= 4
2329582.13020863724318.4575541322329566.57030346724395.277812078
2329799.32448916724508.6118246132329947.18504664724616.928279512
#Sta/Elev= 30
       0 1994.74    10.8 1993.73    35.4 1989.05    68.1 1978.65    72.2  1976.5
    78.4 1969.26      81 1968.52      90 1968.62   107.9 1957.25   110.1 1956.49
   142.5 1955.38   146.9 1954.38   154.41951.078   158.8 1950.35   176.7  1950.1
   182.91951.045   191.4 1954.54   195.8 1955.03   221.6 1956.31   258.1 1955.91
   324.9 1957.91   338.2 1960.42     345 1963.27   358.3 1970.85   372.6 1980.73
   404.1 2000.04   461.3 2029.84   475.6 2036.81   501.9 2047.04   520.6 2051.34
#Mann= 5, -1 ,  0
       0     0.1       0      10    0.06       0   154.4   0.045       0
   182.9    0.06       0  308.38     0.1       0
#XS Ineff= 2 , 0
                          291.98          1972.3
Permanent Ineff=
       F       F
Bank Sta=154.4,182.9
XS Rating Curve= 0 ,0
Exp/Cntr(USF)=0,0
Exp/Cntr=0.3,0.1

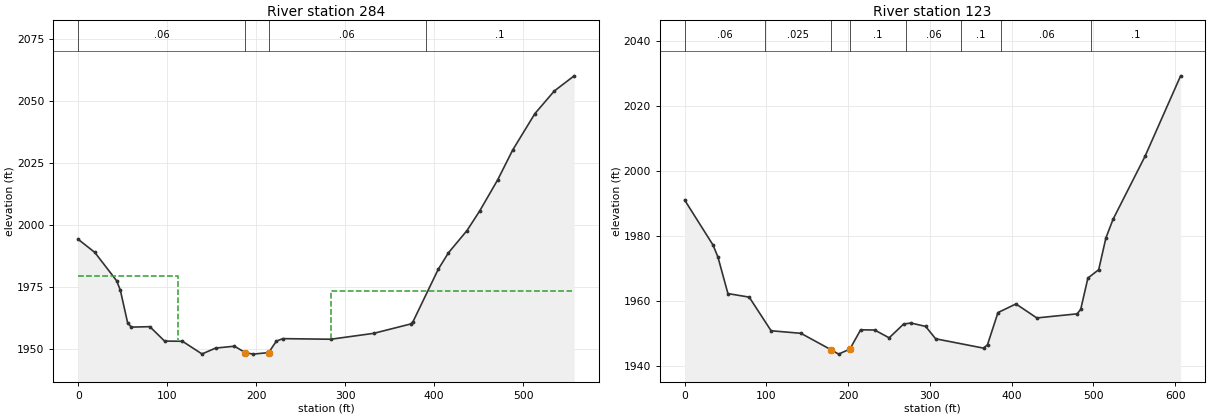
Type RM Length L Ch R = 1 ,284     ,136.3,160.5,167.8
BEGIN DESCRIPTION:
Structure XS 2
END DESCRIPTION:
XS GIS Cut Line= 5
2329549.56861787724343.6251542622329520.34701766724448.072357259
2329639.11935863724502.3534121852329759.47097518 724555.65198523
2329919.36669432724651.933278474
#Sta/Elev= 30
       0 1994.38    18.6 1989.12    43.1 1977.72    47.3 1973.94    55.6 1960.63
    59.8 1959.01    80.5 1959.18    97.1 1953.37   117.1 1953.31   139.1 1948.19
   154.4 1950.56   175.6 1951.31   187.71948.724   196.7 1948.12     2141948.748
   222.6 1953.33   229.9 1954.36   283.9 1954.12   332.1  1956.5   373.6 1960.27
   376.2  1961.2   404.6 1982.32     416 1988.93   436.9 1997.92   451.2 2005.84
   471.4 2018.36   488.2 2030.34   513.2 2045.03   534.9 2054.11   557.3 2060.25
#Mann= 4, -1 ,  0
       0    0.06       0   187.7   0.045       0     214    0.06       0
  390.67     0.1       0
#XS Ineff= 2 , 0
          112.27 1979.67  283.94         1973.37
Permanent Ineff=
       F       F
Bank Sta=187.7,214
XS Rating Curve= 0 ,0
Exp/Cntr(USF)=0,0
Exp/Cntr=0.3,0.1

Type RM Length L Ch R = 1 ,123     ,,,
BEGIN DESCRIPTION:
Structure XS 1
END DESCRIPTION:
XS GIS Cut Line= 5
2329521.34409436 724334.981520342329477.97646969724412.453213889
2329456.18595064724543.0210643162329480.16494159724593.996738798
2329779.20021906724731.395325539
#Sta/Elev= 30
       0 1991.04    34.8 1977.14    40.7 1973.47    52.9 1962.24    78.9 1961.15
   105.7 1950.79   142.2    1950   178.7 1944.98   188.3 1943.59  202.151945.177
   215.2 1951.08   232.4 1951.02   250.1 1948.61   267.7 1952.84   276.6 1953.18
   294.7 1952.13     307 1948.31   365.5 1945.44   370.4  1946.5   383.2 1956.39
   405.2 1959.05   430.7 1954.74     480    1956   484.4 1957.38   493.2 1967.02
   506.4  1969.6   515.2 1979.38     524 1985.15     563  2004.5   606.6 2029.32
#Mann= 8, -1 ,  0
       0    0.06       0   98.78   0.025       0   178.7   0.045       0
  202.15     0.1       0  271.16    0.06       0  337.49     0.1       0
  387.49    0.06       0  497.49     0.1       0
Bank Sta=178.7,202.15
XS Rating Curve= 0 ,0
Exp/Cntr(USF)=0,0
Exp/Cntr=0.3,0.1
LCMann Table=0

Chan Stop Cuts=-1
Use User Specified Reach Order=0
Composite Channel Slope=5